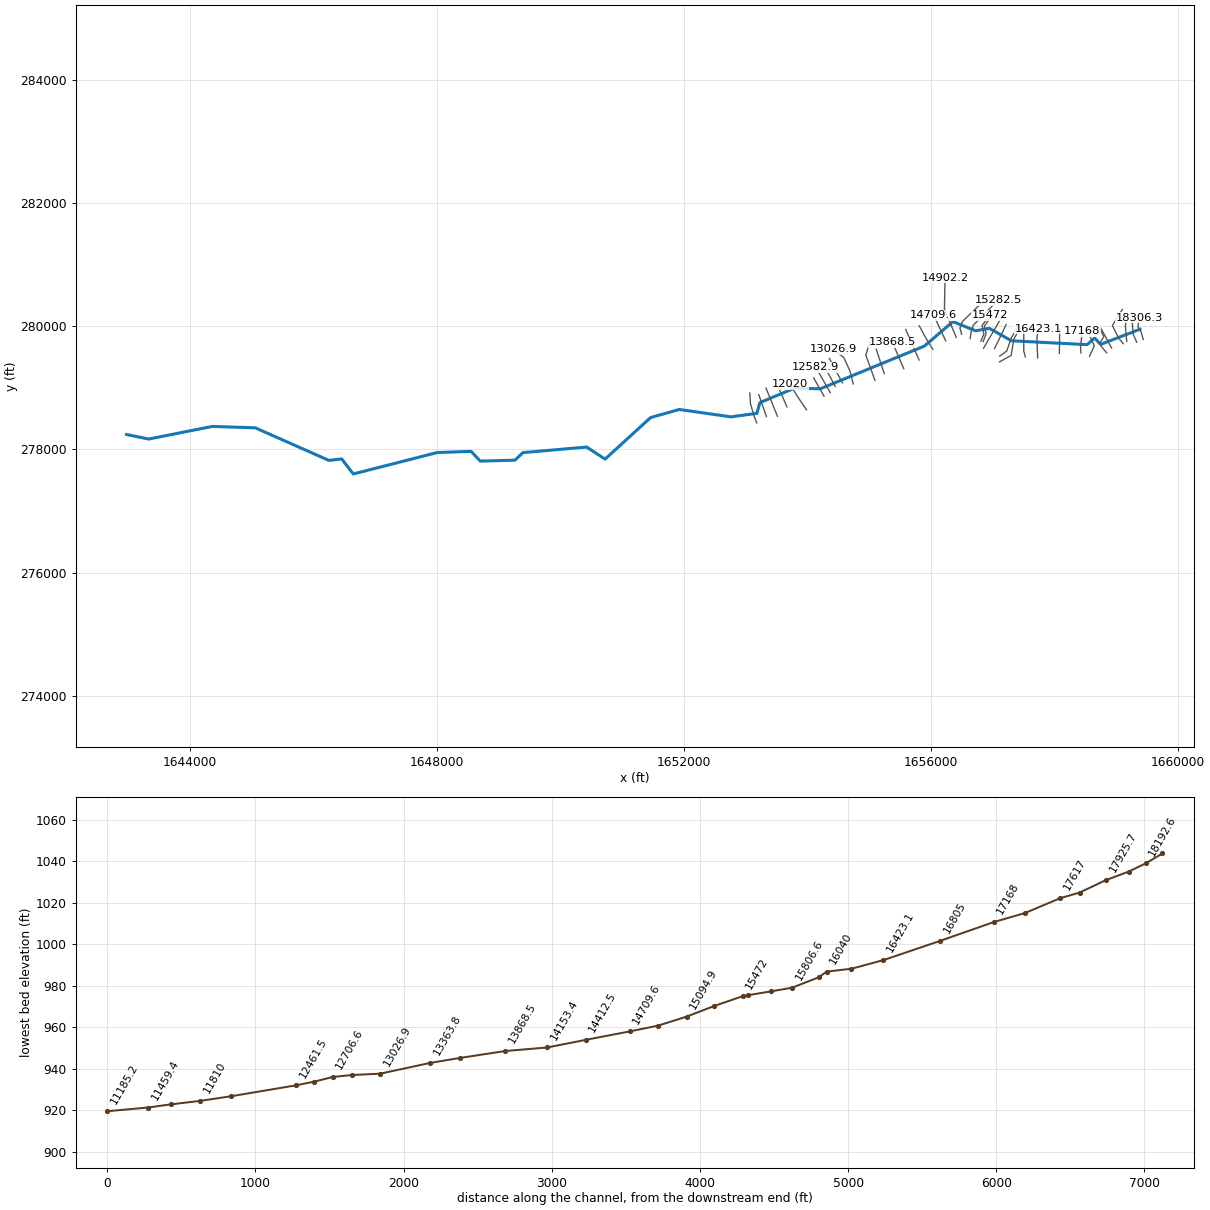
--- BFLCLFFRK.prj (project) ---

Proj Title=BFLCLFFRK
Current Plan=p01
Default Exp/Contr=0,0
English Units
Geom File=g01
Flow File=f01
Plan File=p01
BEGIN DESCRIPTION:
END DESCRIPTION:
DSS Export Rating Curves= 0
DSS Export Rating Curve Sorted= 0
DSS Export Volume Flow Curves= 0
DXF OffsetX= 0
DXF OffsetY= 0
DXF ScaleX= 0
DXF ScaleY= 0

--- BFLCLFFRK.p01 (plan) ---

Plan Title=Floodplain
Program Version=4.00
Geom File=g01
Flow File=f01
K Sum by GR=0
Std Step Tol=0.01
Critical Tol=0.01
Num of Std Step Trials=20
Max Error Tol=0.3
Flow Tol Ratio=0.001
Split Flow NTrial=30
Split Flow Tol=0.02
Split Flow Ratio=0.02
Log Output Level=0
Friction Slope Method=1
Unsteady Friction Slope Method=2
Unsteady Bridges Friction Slope Method=1
Global Log Level=0
CheckData=False
Run HTab=0
Run UNet=0
Run PostProcess=0
UNET Theta=0
UNET Theta Warmup=0
UNET ZTol=0
UNET ZSATol=0
UNET MxIter=0
UNET MaxInSteps=0
UNET DtIC=0
UNET DtMin=0
UNET MaxCRTS=0
UNET WFStab=0
UNET SFStab=0
UNET WFX=0
UNET SFX=0
UNET DSS MLevel=0
UNET DZMax Abort=0
UNET Convert EG Bridges=0
UNET Use Existing IB Tables=0
UNET Froude Limit=0
UNET Froude Power=0
Write IC File=0
Echo Input=False
Echo Output=False
Write Detailed=0

--- BFLCLFFRK.f01 (steady flow) ---

Flow Title=NFF Regression Equation
Program Version=4.10
Number of Profiles= 1
Profile Names=P100yr
River Rch & RM=BFLCLFFRK,Main            ,18306.3
113.0275
River Rch & RM=BFLCLFFRK,Main            ,18192.6
113.0275
River Rch & RM=BFLCLFFRK,Main            ,17925.7
137.9818
River Rch & RM=BFLCLFFRK,Main            ,17746.7
145.0681
River Rch & RM=BFLCLFFRK,Main            ,17377.6
212.3144
River Rch & RM=BFLCLFFRK,Main            ,16805
218.9208
River Rch & RM=BFLCLFFRK,Main            ,16206.8
242.6948
River Rch & RM=BFLCLFFRK,Main            ,15806.6
274.4648
River Rch & RM=BFLCLFFRK,Main            ,15282.5
287.3624
River Rch & RM=BFLCLFFRK,Main            ,14902.2
491.4564
River Rch & RM=BFLCLFFRK,Main            ,13562.9
512.3104
River Rch & RM=BFLCLFFRK,Main            ,12837.5
563.7851
River Rch & RM=BFLCLFFRK,Main            ,12582.9
643.3553
River Rch & RM=BFLCLFFRK,Main            ,11614.4
678.3054
River Rch & RM=BFLCLFFRK,Main            ,9685.8
741.0811
River Rch & RM=BFLCLFFRK,Main            ,9249
837.2094
River Rch & RM=BFLCLFFRK,Main            ,8404.8
883.0945
River Rch & RM=BFLCLFFRK,Main            ,7684.1
943.7891
River Rch & RM=BFLCLFFRK,Main            ,5304.5
997.4411
River Rch & RM=BFLCLFFRK,Main            ,4764.8
1115.195
River Rch & RM=BFLCLFFRK,Main            ,362.4
 1228.99
Boundary for River Rch & Prof#=BFLCLFFRK,Main            , 1
Up Type= 0
Dn Type= 3
Dn Slope=0.0036
DSS Import GetInterval= 0
DSS Import GetPeak= 0
DSS Import FillOption= 0

--- BFLCLFFRK.g01 (geometry) ---

Geom Title=USGS 10m DEM
Program Version=4.10

River Reach=BFLCLFFRK       ,Main
Reach XY= 30
     1659380.049      279949.799     1658741.649      279703.825
     1658646.352      279807.233     1658522.668       279699.77
     1657300.426      279762.626     1656939.512      279965.386
     1656720.531      279924.834     1656351.507       280072.85
     1655891.443      279677.466     1654203.055      278983.214
     1653787.395      278993.352     1653226.154      278759.366
     1653177.491      278584.992     1652755.952      278528.219
     1651920.578      278647.848     1651456.029      278516.049
     1650719.691       277842.55     1650420.211      278037.863
     1649388.962      277947.585     1649260.489      277825.189
     1648698.163      277809.911     1648550.246      277968.245
     1648000.446      277948.743     1646643.329      277601.351
      1646455.25      277844.747      1646246.52      277821.882
     1645055.566      278350.023     1644359.139      278373.027
     1643330.905      278168.025     1642970.755      278241.719

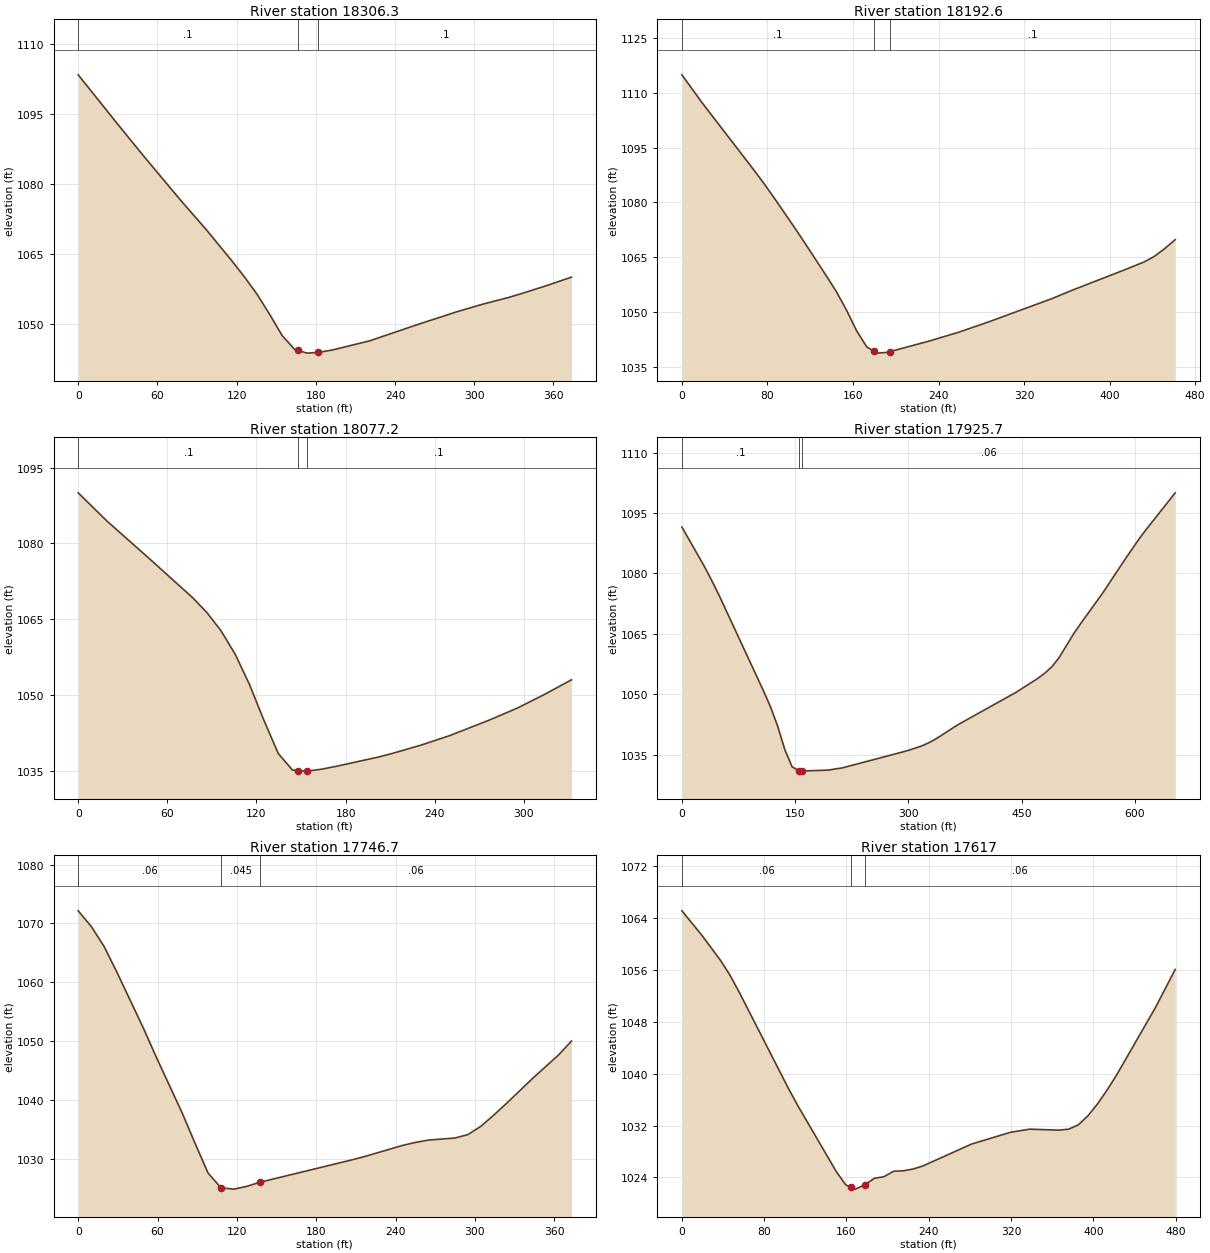
Type RM Length L Ch R = 1 ,18306.3 ,124.3,113.7,103
XS GIS Cut Line= 4
     1659433.521      279783.827     1659398.674      279905.051
     1659348.799      279985.216     1659365.086       280137.49
#Sta/Elev= 23
       0 1103.39    29.1  1093.1    48.5 1086.34    77.6 1076.49      97 1070.19
   116.4  1063.5   126.1 1059.99   135.6 1056.28     145 1052.03   154.5 1047.47
   163.9 1044.52   166.7 1044.28   173.3  1043.7   181.7 1043.84   192.2 1044.35
   220.6 1046.32   258.8 1049.99   287.6 1052.64   306.7 1054.22   325.8 1055.62
   335.4 1056.43   354.6 1058.16   373.7    1060
#Mann= 3 , 0 , 0
       0      .1       0   166.7    .045       0   181.7      .1       0
Bank Sta=166.7,181.7
XS Rating Curve= 0 ,0
Exp/Cntr=0.3,0.1

Type RM Length L Ch R = 1 ,18192.6 ,115.5,115.4,115.4
XS GIS Cut Line= 4
     1659327.162      279738.176     1659270.517      279870.866
     1659255.482      280042.837     1659258.265      280187.258
#Sta/Elev= 26
       0 1114.85    19.2 1107.11    67.3 1088.88      77 1085.07    86.6 1081.12
   105.8 1072.97   115.4 1068.77   134.7 1060.14   144.3 1055.75   153.9 1050.65
   163.5 1044.93     173 1040.54   179.6 1039.39   182.6 1038.87   192.2 1039.08
   194.6 1039.28   230.6 1042.11   259.4 1044.62   288.1 1047.52   345.8 1053.72
     365 1056.04   413.2 1061.51   432.5 1063.78   442.1 1065.33   451.7 1067.44
   461.4 1069.85
#Mann= 3 , 0 , 0
       0      .1       0   179.6    .045       0   194.6      .1       0
Bank Sta=179.6,194.6
XS Rating Curve= 0 ,0
Exp/Cntr=0.3,0.1

Type RM Length L Ch R = 1 ,18077.2 ,142.9,151.5,160
XS GIS Cut Line= 3
     1659165.155      279750.996     1659143.937      280000.233
     1659153.703      280081.614
#Sta/Elev= 23
       0    1090    19.2 1084.46    48.1 1076.92      77 1069.26    86.6 1066.32
    96.2 1062.68   105.8    1058   115.4    1052   125.1 1044.93   134.7  1038.4
   144.3 1035.12   148.3 1035.04   153.9 1034.92   163.6 1035.29   173.2 1035.84
     202  1037.7   211.7 1038.44   230.9 1040.08   250.1 1041.95   277.5 1045.11
   295.7 1047.41   313.9  1050.1   332.1    1053
#Mann= 3 , 0 , 0
       0      .1       0   148.3    .045       0   153.9      .1       0
Bank Sta=148.3,153.9
XS Rating Curve= 0 ,0
Exp/Cntr=0.3,0.1

Type RM Length L Ch R = 1 ,17925.7 ,178.2,179,179.7
XS GIS Cut Line= 4
     1659109.215       279714.86      1659035.43      279806.006
     1658933.105      280010.623     1659095.547      280271.489
#Sta/Elev= 30
       0 1091.49    29.3 1081.87    39.1 1078.38    48.9 1074.68   107.5 1051.04
   117.3 1046.87   126.8 1042.08   136.3 1036.24   145.9 1031.98   155.4 1030.88
     159 1030.91   193.5 1031.13   212.6 1031.69   298.4 1035.94   317.4 1037.11
     327 1037.92   336.5 1038.89   365.2 1042.36   442.1  1050.4   470.9 1053.84
   480.5 1055.18   490.1 1056.81   499.7 1059.09   518.9 1064.99   528.5  1067.6
   557.3 1075.09   586.1 1083.24   605.3 1088.49   614.9 1090.88   653.4 1099.99
#Mann= 3 , 0 , 0
       0      .1       0   155.4    .045       0     159     .06       0
Bank Sta=155.4,159
XS Rating Curve= 0 ,0
Exp/Cntr=0.3,0.1

Type RM Length L Ch R = 1 ,17746.7 ,132.7,129.7,124.6
XS GIS Cut Line= 2
     1658921.498      279644.331     1658743.622      279972.229
#Sta/Elev= 26
       0 1072.13     9.8  1069.5    19.6 1066.07    29.4 1061.64    49.1 1052.29
    58.9 1047.34    78.5 1037.84    88.4 1032.61    98.2 1027.57     108 1025.06
   117.8 1024.84   127.6 1025.32   137.4 1026.01   206.2 1029.77     216 1030.34
   245.4 1032.28   255.2 1032.79     265 1033.18   284.7 1033.52   294.5 1034.09
   304.3 1035.49   314.1 1037.39     324 1039.44   343.6 1043.66   363.2 1047.64
     373    1050
#Mann= 3 , 0 , 0
       0     .06       0     108    .045       0   137.4     .06       0
Bank Sta=108,137.4
XS Rating Curve= 0 ,0
Exp/Cntr=0.3,0.1

Type RM Length L Ch R = 1 ,17617   ,234.8,239.5,242.9
XS GIS Cut Line= 5
     1658842.288      279566.206     1658756.917      279666.312
     1658733.781      279726.796      1658795.63      279833.133
     1658719.675      279974.192
#Sta/Elev= 30
       0 1065.15    18.8  1061.5    37.6 1057.49      47 1055.15    56.4 1052.38
   103.4 1037.78   112.8 1035.04   150.1 1024.89   159.3 1022.84   164.5 1022.47
   168.6 1022.18   177.8 1022.85   187.1 1023.85   196.3 1024.09   205.8 1024.94
   215.2 1025.01   224.7 1025.28   234.2 1025.75   281.5 1029.13   319.3 1030.95
   338.2 1031.44   366.5 1031.29   375.9 1031.43   385.3 1032.09   394.7 1033.49
   404.2 1035.36   413.6 1037.53     423  1039.9   460.7  1050.3   479.6  1056.1
#Mann= 3 , 0 , 0
       0     .06       0   164.5    .045       0   177.8     .06       0
Bank Sta=164.5,177.8
XS Rating Curve= 0 ,0
Exp/Cntr=0.3,0.1

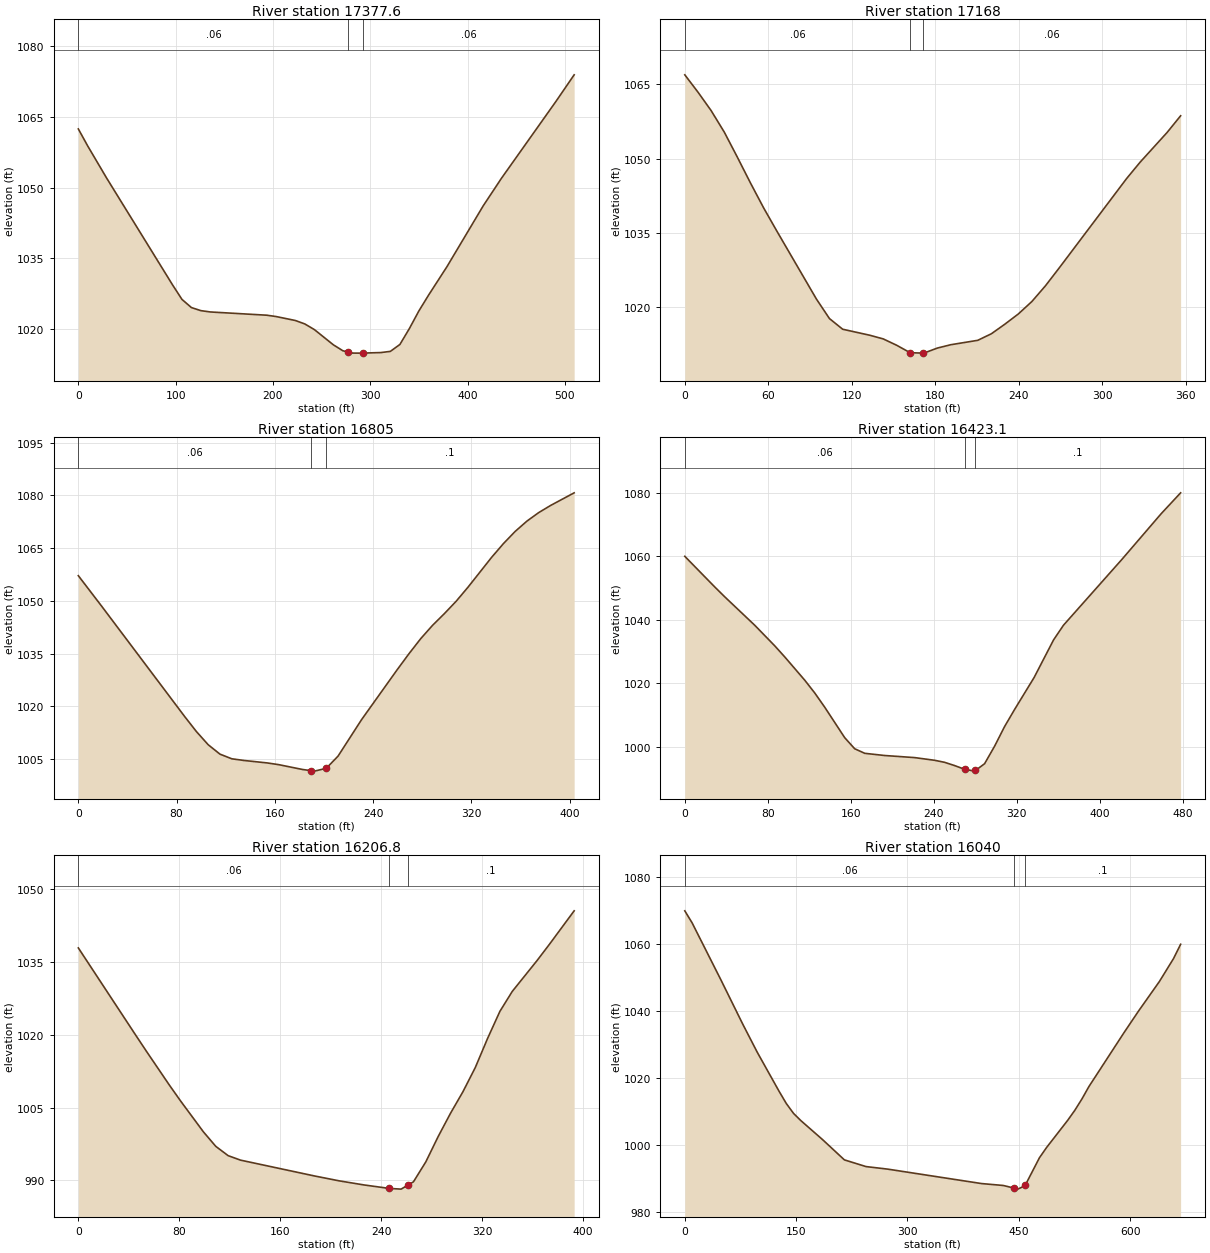
Type RM Length L Ch R = 1 ,17377.6 ,222.6,209.6,196.7
XS GIS Cut Line= 4
     1658563.425      279511.952     1658640.465      279679.053
      1658564.51      279848.324      1658560.17      279988.298
#Sta/Elev= 30
       0  1062.4     9.7 1058.78      29 1052.04    96.8 1029.43   106.5 1026.35
   116.2 1024.62   125.9 1023.97   135.6 1023.69   193.8    1023   203.5 1022.71
   223.1 1021.88   232.8 1021.15   242.6 1019.96   262.1 1016.74   271.9 1015.48
   277.5  1015.2   281.6 1014.99   291.4 1014.98   292.5 1014.99     311  1015.1
   320.7 1015.35   330.5 1016.81   340.2 1020.16     350  1023.9   359.8 1027.19
   378.9 1033.28   416.2 1046.16   434.9 1051.97   490.9 1068.23   509.6 1073.85
#Mann= 3 , 0 , 0
       0     .06       0   277.5    .045       0   292.5     .06       0
Bank Sta=277.5,292.5
XS Rating Curve= 0 ,0
Exp/Cntr=0.3,0.1

Type RM Length L Ch R = 1 ,17168   ,359.1,363,366.3
XS GIS Cut Line= 3
     1658423.668      279565.121     1658417.158      279678.402
     1658448.408      279919.287
#Sta/Elev= 30
       0 1066.92     9.5 1063.41    18.9  1059.7    28.4 1055.33    37.8 1050.26
    47.3    1045    56.7    1040    66.2 1035.31    94.6 1021.59     104 1017.63
   113.5 1015.48   132.9 1014.27   142.6 1013.53   152.3 1012.24     162 1010.73
     171 1010.66   171.8 1010.65   181.5 1011.67   191.2 1012.35   210.6 1013.24
   220.4 1014.57   230.1 1016.51   239.8 1018.58   249.5 1021.09   259.2 1024.25
   268.9 1027.79   317.5 1045.92   327.2 1049.23   346.7 1055.27   356.4 1058.64
#Mann= 3 , 0 , 0
       0     .06       0     162    .045       0     171     .06       0
Bank Sta=162,171
XS Rating Curve= 0 ,0
Exp/Cntr=0.3,0.1

Type RM Length L Ch R = 1 ,16805   ,380.5,381.9,383.2
XS GIS Cut Line= 2
      1658074.92      279557.336     1658080.706      279960.934
#Sta/Elev= 30
       0 1057.15    19.2 1048.38    86.5 1017.13    96.1 1012.84   105.7 1009.09
   115.3 1006.41   124.9 1005.09   134.6 1004.62   153.8 1003.91   163.4  1003.4
   182.6 1002.04   189.1 1001.73   192.2 1001.58   201.8 1002.38   211.4 1005.84
   230.6 1016.24   259.5 1030.39   269.1 1034.94   278.7 1039.24   288.3 1043.02
   297.9 1046.34   307.5 1049.86   317.2 1053.88   336.4 1062.36     346 1066.26
   355.6 1069.74   365.2 1072.68   374.8  1075.1   384.4 1077.11   403.6 1080.71
#Mann= 3 , 0 , 0
       0     .06       0   189.1    .045       0   201.8      .1       0
Bank Sta=189.1,201.8
XS Rating Curve= 0 ,0
Exp/Cntr=0.3,0.1

Type RM Length L Ch R = 1 ,16423.1 ,217,216.3,215.3
XS GIS Cut Line= 3
     1657723.465      279484.519     1657711.429        279802.1
     1657733.307      279960.565
#Sta/Elev= 30
       0    1060    28.9 1050.34    38.5 1047.24    67.4 1038.29    86.7  1031.8
    96.3 1028.32   115.6 1020.98   125.2 1016.97   134.8  1012.5   154.1 1002.88
   163.7  999.39   173.4  997.95   192.6  997.26   221.5   996.6   240.8  995.75
   250.4  995.11     260  994.09   269.7  992.92   279.3  992.34   280.1  992.54
   288.9  994.68   298.6 1000.23   308.2  1006.4   317.8 1011.76   336.6 1021.82
   355.4 1033.69   364.9 1038.29   421.3 1059.06     459  1073.4   477.8    1080
#Mann= 3 , 0 , 0
       0     .06       0   269.7    .045       0   280.1      .1       0
Bank Sta=269.7,280.1
XS Rating Curve= 0 ,0
Exp/Cntr=0.3,0.1

Type RM Length L Ch R = 1 ,16206.8 ,170.5,166.8,163.3
XS GIS Cut Line= 3
     1657523.787      279501.202     1657498.335      279596.971
     1657498.512      279890.646
#Sta/Elev= 27
       0 1037.94      45 1020.13      54  1016.6    72.1 1009.66    81.1 1006.34
    99.1    1000   108.9  997.01   118.7  995.09   128.5  994.17   187.2   990.9
   206.8  989.89   226.4  989.05   246.2  988.34   255.7  988.19   261.2  989.04
   265.5   989.7   275.3  993.82   285.1  999.05   294.9 1003.86   304.7 1008.28
   314.5 1013.28   324.2 1019.26     334 1024.87   343.8 1028.98   363.4 1035.33
   373.2 1038.68   392.8 1045.59
#Mann= 3 , 0 , 0
       0     .06       0   246.2    .045       0   261.2      .1       0
Bank Sta=246.2,261.2
XS Rating Curve= 0 ,0
Exp/Cntr=0.3,0.1

Type RM Length L Ch R = 1 ,16040   ,57.9,54.6,50.4
XS GIS Cut Line= 4
     1657106.827      279421.054     1657294.745      279525.555
     1657336.411      279785.103     1657426.621      279952.544
#Sta/Elev= 30
       0    1070     9.8 1066.43    48.9 1049.25    78.2 1036.08    97.7 1027.69
   127.1 1016.03   136.8 1012.39   146.6 1009.42   156.4 1007.28   185.7 1001.59
     215  995.55   244.2  993.54   273.4  992.78     400  988.46   429.2  987.89
     444  987.09   448.7   986.8   458.4  987.82     459  988.07   477.9  996.19
   487.4  999.22   515.9 1007.36   525.4 1010.32     535 1013.71   544.5 1017.45
     592 1033.64     611 1039.91   639.6  1048.9   658.6 1055.75   668.1    1060
#Mann= 3 , 0 , 0
       0     .06       0     444    .045       0     459      .1       0
Bank Sta=444,459
XS Rating Curve= 0 ,0
Exp/Cntr=0.3,0.1

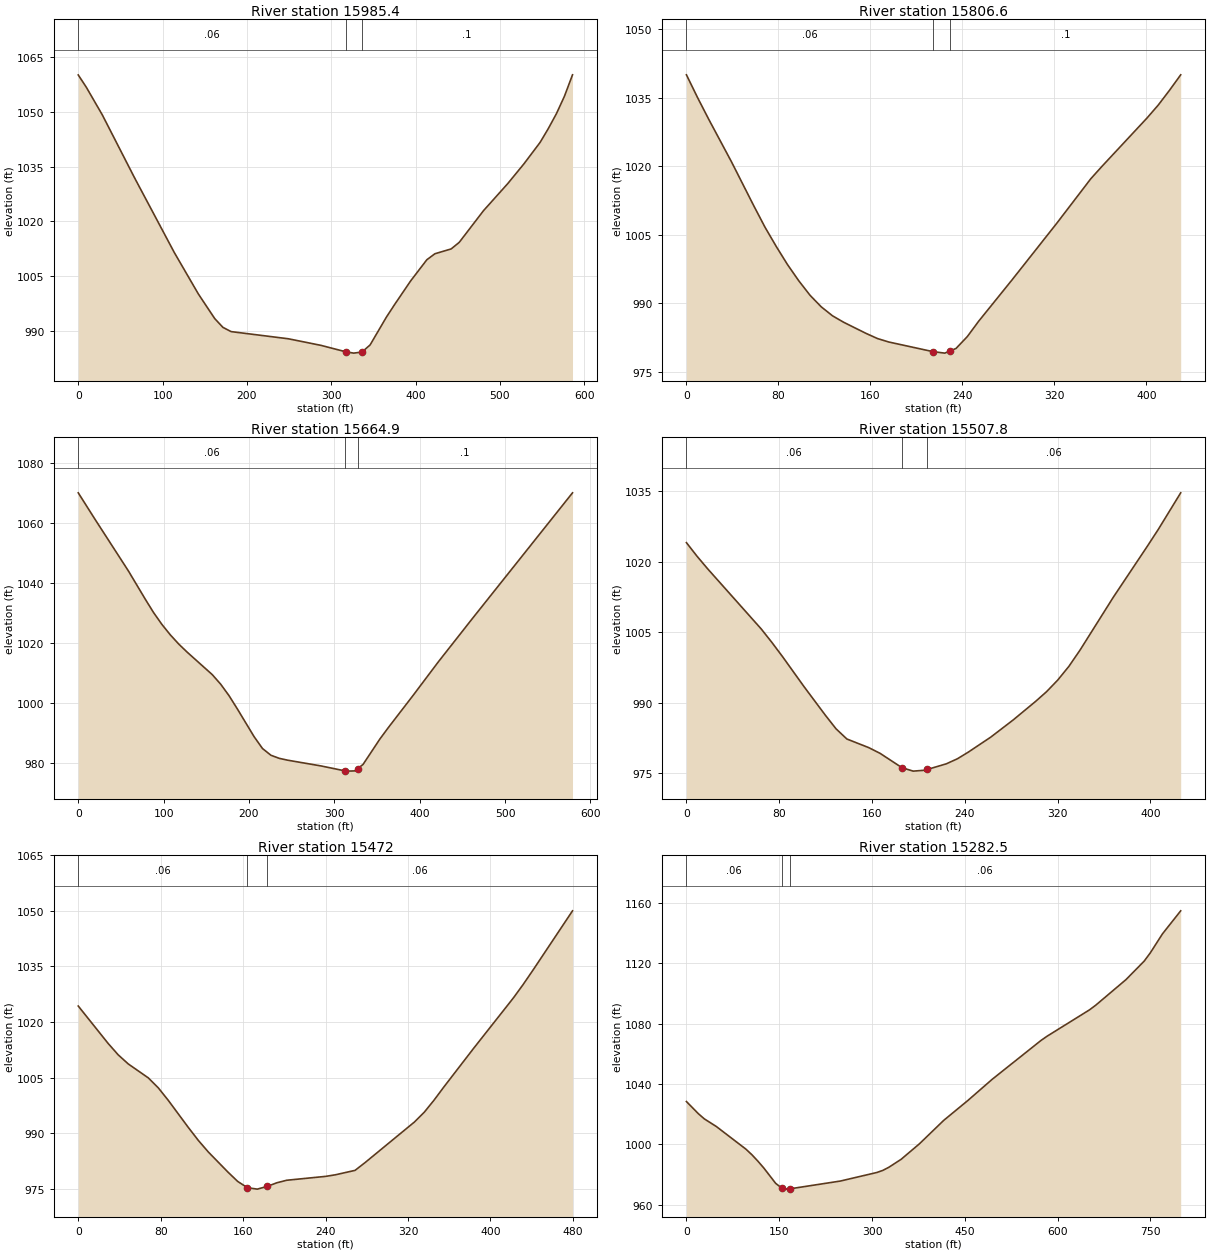
Type RM Length L Ch R = 1 ,15985.4 ,182.6,178.9,175.8
XS GIS Cut Line= 4
     1657109.845      279513.027     1657224.432      279597.603
     1657292.141       279799.86     1657406.512       279999.76
#Sta/Elev= 30
       0 1060.02     9.5 1056.69    28.5 1049.13    66.5 1032.04   113.9 1011.51
   142.4  1000.2   161.8  993.48   171.5  991.08   181.2  989.92   249.1  987.96
   287.8  986.16   316.9  984.42   326.5  984.04   336.3  984.33     346  986.27
   365.3  993.86   374.9  997.25   394.1 1003.77   413.3 1009.55   422.9 1011.19
   442.1  1012.5   451.7  1014.3   480.5 1022.96   509.2 1030.34   528.4 1035.74
   547.6 1041.61   557.2 1045.33   566.8 1049.39   576.4 1054.19     586 1060.06
#Mann= 3 , 0 , 0
       0     .06       0   316.9    .045       0   336.3      .1       0
Bank Sta=316.9,336.3
XS Rating Curve= 0 ,0
Exp/Cntr=0.3,0.1

Type RM Length L Ch R = 1 ,15806.6 ,143.5,141.6,139.7
XS GIS Cut Line= 2
     1657026.578      279635.663      1657211.66       280023.69
#Sta/Elev= 30
       0    1040     9.8 1034.95    19.5 1030.21    39.1 1020.99    58.6 1011.31
    68.4  1006.6    78.2 1002.38    87.9  998.45    97.7   994.9   107.5  991.73
   117.2  989.21     127  987.24   136.8  985.81   156.3  983.37   166.1  982.26
   175.9   981.5   214.5  979.38   224.7  979.06   229.5  979.56   234.5  980.09
   244.3  982.68     254  985.99   283.4  995.16   322.4 1007.59   351.7 1017.24
   361.5 1019.98   400.6 1030.54   410.4 1033.39   420.1 1036.59   429.9    1040
#Mann= 3 , 0 , 0
       0     .06       0   214.5    .045       0   229.5      .1       0
Bank Sta=214.5,229.5
XS Rating Curve= 0 ,0
Exp/Cntr=0.3,0.1

Type RM Length L Ch R = 1 ,15664.9 ,137.9,157.1,176.2
XS GIS Cut Line= 2
     1656847.491      279642.921     1657139.035      280143.277
#Sta/Elev= 30
       0    1070    19.6  1061.2    58.9 1043.92    78.5 1034.59    88.3 1030.09
    98.2  1026.1     108 1022.65   117.8 1019.61   127.6 1016.93     157 1009.45
   166.9 1006.25   176.7 1002.42   186.5  997.98   206.1  988.75   215.9  984.82
   225.8  982.58   235.6  981.55   245.4  980.94   284.6  979.02   312.5  977.38
   314.1   977.3   323.9  977.37   327.5  978.17   333.7  979.54   353.4  987.99
   363.2  991.76   392.6 1002.62     422 1013.74   461.3 1027.95   579.1    1070
#Mann= 3 , 0 , 0
       0     .06       0   312.5    .045       0   327.5      .1       0
Bank Sta=312.5,327.5
XS Rating Curve= 0 ,0
Exp/Cntr=0.3,0.1

Type RM Length L Ch R = 1 ,15507.8 ,36.5,35.8,35.1
XS GIS Cut Line= 4
     1656841.837      279749.947     1656890.144      279879.504
     1656859.198      279999.513     1656955.769      280131.891
#Sta/Elev= 30
       0 1024.07     9.2 1021.16    18.4 1018.47    64.5 1005.69    73.7 1002.82
      83  999.75   101.4  993.41   119.8  987.32     129  984.43   138.3  982.27
   157.3  980.42   166.9  979.22   185.9  976.15   195.5  975.43     205  975.61
   207.6  975.78   224.1  976.99   233.6  978.06   243.1  979.49   262.2  982.64
   281.5  986.29   300.8  990.23   310.4  992.33     320  994.79   329.7  997.73
   339.3 1001.19   368.2 1012.53   397.2 1023.26   406.8  1026.9   426.1 1034.68
#Mann= 3 , 0 , 0
       0     .06       0   185.9    .045       0   207.6     .06       0
Bank Sta=185.9,207.6
XS Rating Curve= 0 ,0
Exp/Cntr=0.3,0.1

Type RM Length L Ch R = 1 ,15472   ,202.5,189.5,176.4
XS GIS Cut Line= 4
     1656803.859      279756.457     1656853.338       279872.56
     1656822.588      280011.598     1656951.192      280178.919
#Sta/Elev= 30
       0 1024.32    29.1  1014.2    38.8 1011.15    48.5 1008.71      68 1004.94
    77.7 1002.25    87.4  998.87   106.8  991.58   116.5  988.09   126.2  984.96
   145.2  979.55   154.7  977.02   164.2  975.32   173.7  974.94   183.2  975.66
   192.7  976.65   202.2  977.33   240.1  978.38   249.6  978.81   268.6     980
   278.2  982.07   326.2  993.04   335.8   995.7   345.3  998.96   354.9 1002.54
   383.7 1012.93   422.1 1026.46   431.7 1030.13   441.3 1034.03   479.6    1050
#Mann= 3 , 0 , 0
       0     .06       0   164.2    .045       0   183.2     .06       0
Bank Sta=164.2,183.2
XS Rating Curve= 0 ,0
Exp/Cntr=0.3,0.1

Type RM Length L Ch R = 1 ,15282.5 ,187.6,187.7,187.7
XS GIS Cut Line= 4
     1656630.943      279797.733     1656648.304      279921.865
     1656684.762      280019.088     1657084.309        280425.5
#Sta/Elev= 30
       0 1028.34    19.3 1020.29    28.9 1016.86    48.2 1011.84    96.4  996.72
   106.1  992.98   115.7  988.75   125.3  984.19   144.2  974.16   153.7  971.09
   163.1   970.3   166.8  970.47   248.8  975.65   307.8  981.32   317.6  982.73
   327.4  984.82   347.1  990.06   376.6  1000.3   415.9 1015.84   455.2 1029.12
   494.5 1043.14   573.1 1068.79   582.9 1071.59   651.7 1089.12   661.5 1092.12
   710.7 1109.18   740.1 1121.43     750 1126.91   769.6 1139.46   799.1 1154.74
#Mann= 3 , 0 , 0
       0     .06       0   153.7    .045       0   166.8     .06       0
Bank Sta=153.7,166.8
XS Rating Curve= 0 ,0
Exp/Cntr=0.3,0.1

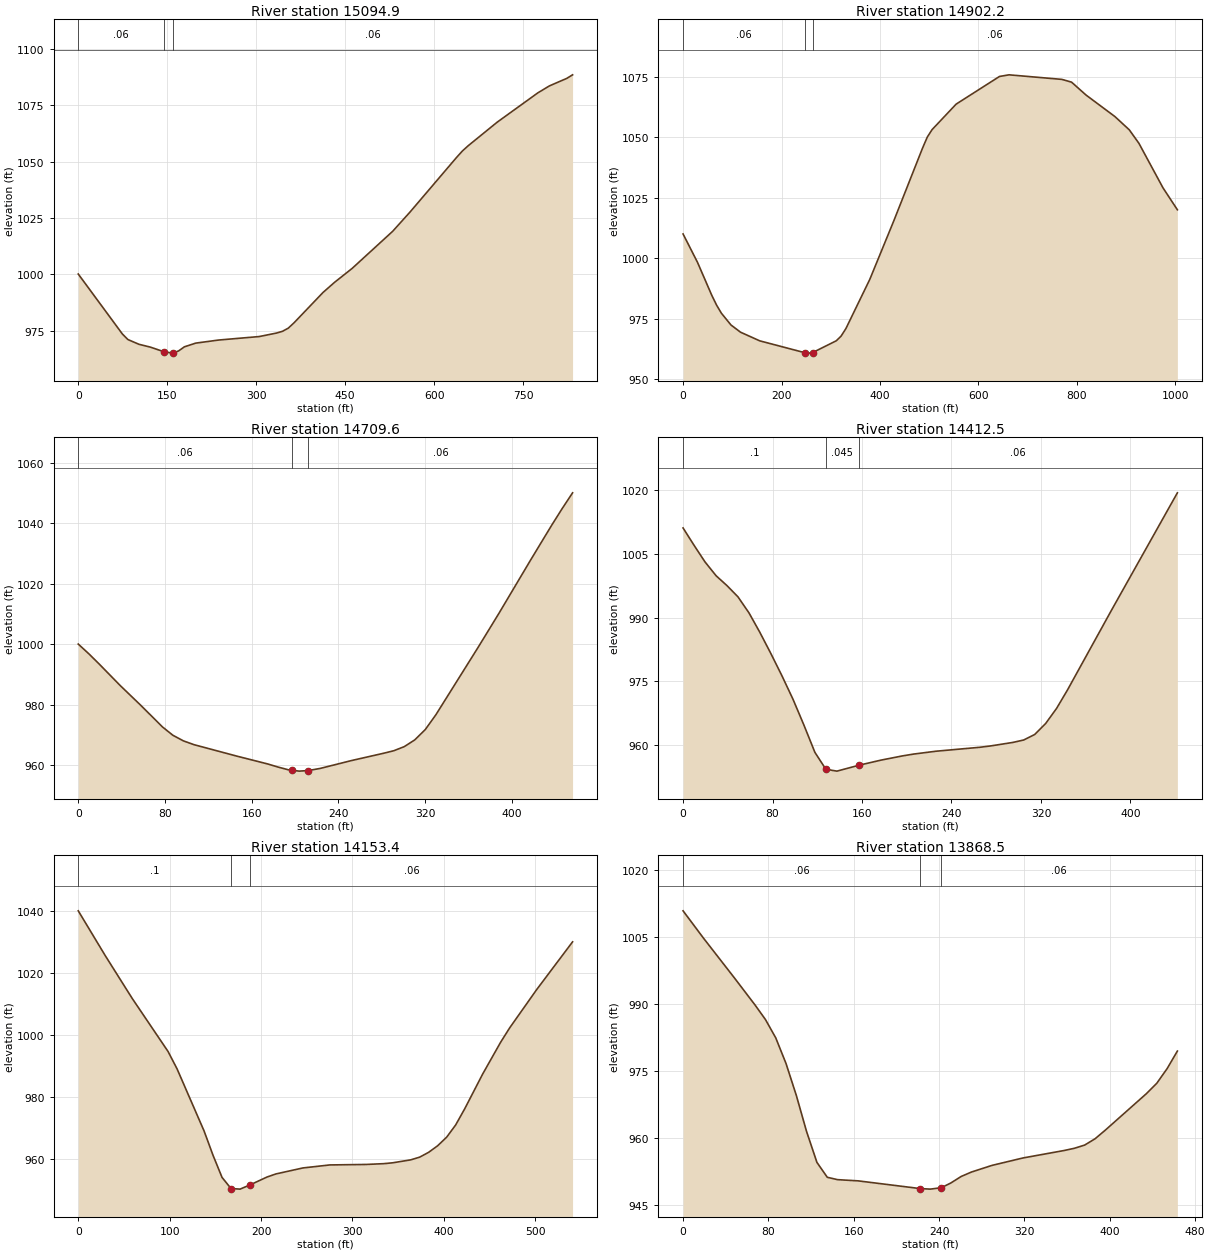
Type RM Length L Ch R = 1 ,15094.9 ,175.2,192.6,210.1
XS GIS Cut Line= 4
     1656492.054      279869.565     1656466.012      279968.523
     1656505.943      280076.162     1656948.651      280504.982
#Sta/Elev= 30
       0 1000.21    74.4  973.63    83.7  971.17   102.3  969.06   121.5  967.81
   145.1   965.7   159.7  965.14   160.1  965.18   169.3  966.13   178.9  967.93
     198  969.57   236.7  970.94   305.2  972.49   334.5  974.05   344.3  974.81
   354.1   976.2   363.9   978.6   412.8  992.05   432.4  996.58   461.7 1002.67
   530.2 1019.16   559.6 1027.74   637.8 1051.87   647.6 1054.72   657.4 1057.06
   706.3 1067.51   774.8  1080.5   794.3 1083.59   823.7 1086.94   833.5 1088.52
#Mann= 3 , 0 , 0
       0     .06       0   145.1    .045       0   160.1     .06       0
Bank Sta=145.1,160.1
XS Rating Curve= 0 ,0
Exp/Cntr=0.3,0.1

Type RM Length L Ch R = 1 ,14902.2 ,191.6,192.7,193.6
XS GIS Cut Line= 3
     1656404.583      279819.229     1656214.017      280277.343
     1656223.669      280785.397
#Sta/Elev= 30
       0    1010    29.2  998.34    58.4  984.65    68.1  980.62    77.8   977.3
    97.3  972.43   116.8  969.44   155.7  965.88   248.2  960.93     253   960.8
   263.2  961.02   311.3   965.9     321  967.81   330.8  970.92   379.4  991.26
   428.1  1015.4   486.4 1045.38   496.2    1050   505.9 1053.08   554.8 1063.61
   642.8 1075.03   662.3 1075.71   769.8 1073.82   789.3 1072.69   818.6 1067.38
   877.3 1058.49   906.6    1053   926.1 1047.45     975 1029.07  1004.3 1019.99
#Mann= 3 , 0 , 0
       0     .06       0   248.2    .045       0   263.2     .06       0
Bank Sta=248.2,263.2
XS Rating Curve= 0 ,0
Exp/Cntr=0.3,0.1

Type RM Length L Ch R = 1 ,14709.6 ,294.4,297.1,299.5
XS GIS Cut Line= 2
     1656234.551      279762.827     1656040.414      280175.368
#Sta/Elev= 30
       0    1000     9.7  996.81    19.4  993.37    38.8  986.26    58.2  979.57
    77.6  972.63    87.3  969.85      97     968   106.7  966.75   145.5  963.03
   174.6  960.38   184.3  959.34     194  958.42   197.2  958.28   203.7     958
   212.2  958.19   223.1  958.89   252.2  961.51   281.3  963.88     291  964.74
   300.7   966.1   310.4  968.34   320.1  971.76   329.8  976.62   368.6  998.81
     388 1010.17   417.1 1027.72   436.5 1039.21   446.2 1044.73   455.9    1050
#Mann= 3 , 0 , 0
       0     .06       0   197.2    .045       0   212.2     .06       0
Bank Sta=197.2,212.2
XS Rating Curve= 0 ,0
Exp/Cntr=0.3,0.1

Type RM Length L Ch R = 1 ,14412.5 ,262.2,259.1,256.1
XS GIS Cut Line= 3
     1656026.776      279623.037      1655908.72      279815.746
     1655805.768        280005.7
#Sta/Elev= 30
       0 1011.05     9.8 1006.99    19.6 1003.08    29.5  999.84    39.3   997.5
    49.1  994.87      59  991.08    68.8  986.47    78.6  981.51    88.4  976.34
    98.3  970.82   108.1  964.73   117.9  958.34   127.7  954.37   137.6  953.94
   157.2  955.32   176.9  956.52   196.5  957.53   206.3  957.95     226  958.61
   265.3  959.54   275.1  959.86   294.7  960.67   304.6  961.25   314.4  962.54
   324.2  965.12     334  968.68   343.8  973.03   383.1  991.74     442  1019.3
#Mann= 3 , 0 , 0
       0      .1       0   127.7    .045       0   157.2     .06       0
Bank Sta=127.7,157.2
XS Rating Curve= 0 ,0
Exp/Cntr=0.3,0.1

Type RM Length L Ch R = 1 ,14153.4 ,284.9,284.8,284.7
XS GIS Cut Line= 2
     1655803.732      279451.046     1655587.664      279946.748
#Sta/Elev= 30
       0    1040    29.5 1025.57      59 1011.77    98.3  994.63   108.2  988.99
   137.6  969.07   147.5  961.15   157.3  954.06   167.1  950.48     177  950.28
   188.3  951.69   206.5  954.18   216.3  955.18   245.8  957.11   275.3  958.08
   314.6  958.23   334.3  958.49   344.1  958.77   363.8  959.72   373.6   960.6
   383.4  962.16   393.3  964.29   403.1  967.05   412.9  970.97   422.8  976.18
   442.4  987.36   462.1  997.64   471.9 1002.23   501.4 1014.56   540.8    1030
#Mann= 3 , 0 , 0
       0      .1       0   167.1    .045       0   188.3     .06       0
Bank Sta=167.1,188.3
XS Rating Curve= 0 ,0
Exp/Cntr=0.3,0.1

Type RM Length L Ch R = 1 ,13868.5 ,307.6,305.7,303.7
XS GIS Cut Line= 2
      1655555.82      279308.735     1655373.526      279734.779
#Sta/Elev= 30
       0 1010.84    19.3 1004.68    48.3  995.78    67.6  989.73    77.2  986.53
    86.9  982.41    96.5  976.69   106.2  969.52   115.8  961.45   125.5  954.55
   135.2  951.22   144.8  950.69   164.1  950.42     222   948.7   231.7  948.57
     242  948.88     251  949.94   260.7   951.4   270.3  952.39   289.6  953.88
   318.6  955.54   357.2  957.21   366.9  957.71   376.5  958.43   386.2  959.83
   395.8  961.76   434.4  969.94   444.1  972.26   453.8  975.54   463.4  979.46
#Mann= 3 , 0 , 0
       0     .06       0     222    .045       0     242     .06       0
Bank Sta=222,242
XS Rating Curve= 0 ,0
Exp/Cntr=0.3,0.1

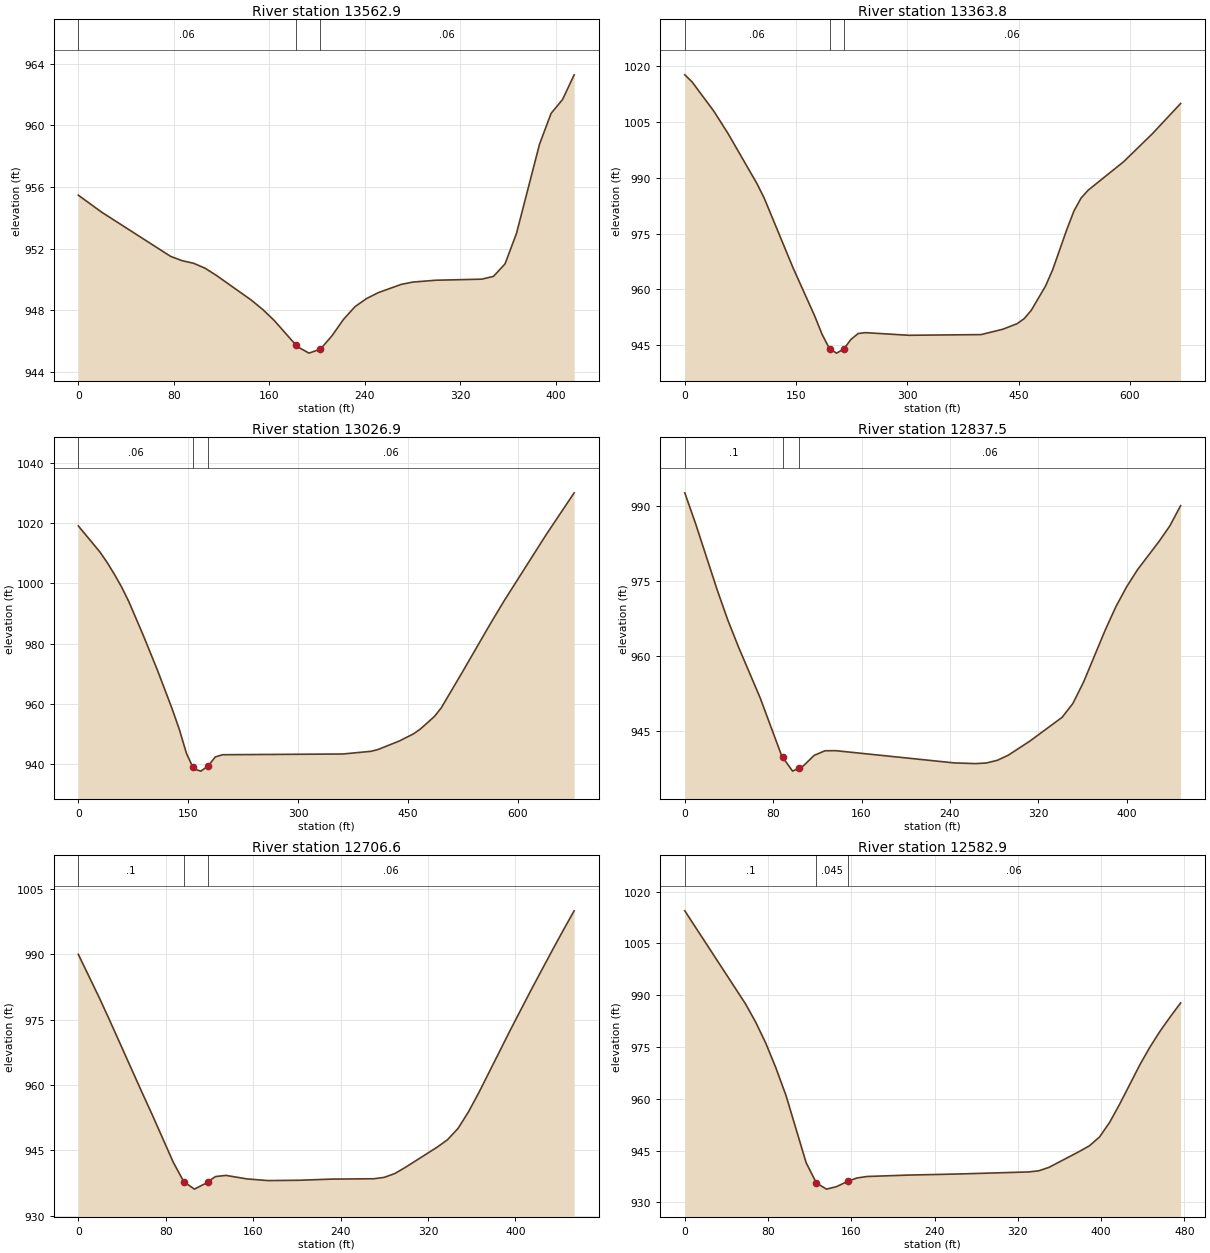
Type RM Length L Ch R = 1 ,13562.9 ,196.5,199.1,201
XS GIS Cut Line= 2
     1655239.177      279230.594     1655110.087      279625.317
#Sta/Elev= 30
       0  955.47    19.3  954.38    77.3   951.5    86.9  951.22    96.6  951.05
   106.2  950.73   115.9  950.25   144.9  948.66   154.5  948.05   164.2  947.33
   182.1  945.76   183.5  945.64   193.2  945.22   202.8  945.48   212.5  946.35
   222.1  947.41   231.8  948.24   241.4  948.76   251.1  949.14   270.4  949.68
   280.1  949.83   299.4  949.95     338  950.02   347.7   950.2   357.4  951.01
     367  952.99   386.3  958.78     396  960.78   405.6  961.68   415.3  963.28
#Mann= 3 , 0 , 0
       0     .06       0   182.1    .045       0   202.8     .06       0
Bank Sta=182.1,202.8
XS Rating Curve= 0 ,0
Exp/Cntr=0.3,0.1

Type RM Length L Ch R = 1 ,13363.8 ,339.2,336.9,334.6
XS GIS Cut Line= 3
     1655089.276      279119.565     1654940.716      279531.972
     1655011.876      279750.782
#Sta/Elev= 30
       0 1017.71     9.7 1015.84      39 1007.98    58.4 1001.89    97.4  988.41
   107.2  984.48   146.1  965.72   175.3  952.76   185.1  947.89   195.1  944.02
   204.6  942.85   214.3  943.95     224  946.55   233.8  948.13   243.5  948.36
     302  947.65   399.4  947.83   428.6  949.27   447.9  950.76   457.5  952.12
   467.1  954.38   486.3  960.89   495.9  965.27     515  976.11   524.6  981.08
   534.2  984.56   543.8  986.68   591.7  994.36   630.1 1001.82   668.4    1010
#Mann= 3 , 0 , 0
       0     .06       0   195.1    .045       0   214.3     .06       0
Bank Sta=195.1,214.3
XS Rating Curve= 0 ,0
Exp/Cntr=0.3,0.1

Type RM Length L Ch R = 1 ,13026.9 ,183.8,189.5,194.9
XS GIS Cut Line= 4
     1654736.845      279062.273     1654684.762      279272.343
     1654583.739      279490.943      1654409.64      279624.681
#Sta/Elev= 30
       0 1019.02    29.5 1010.37    39.4 1006.87    49.2    1003      59  998.79
    68.9  993.93    88.5  982.81   108.2  971.04   127.9  958.43   137.7  951.64
   147.6  943.57   156.4  938.94   157.4  938.41   167.2  937.68   177.1  939.35
   186.9  942.38   196.8  943.12   360.9  943.36   399.4  944.25   409.1  944.85
     438  947.66   457.2     950   466.8  951.63   485.9  955.76   495.4  958.67
   524.1  970.48   562.2  986.48   581.3  994.21   638.6 1016.12   676.8    1030
#Mann= 3 , 0 , 0
       0     .06       0   156.4    .045       0   177.1     .06       0
Bank Sta=156.4,177.1
XS Rating Curve= 0 ,0
Exp/Cntr=0.3,0.1

Type RM Length L Ch R = 1 ,12837.5 ,130.9,130.9,131.1
XS GIS Cut Line= 2
     1654561.993      279079.496     1654351.598      279476.033
#Sta/Elev= 30
       0  992.54     9.8  986.38    29.3   973.2      39  967.13    48.8   961.7
    68.3  951.62    87.8  940.04    88.7  939.76    97.6  937.04   103.7  937.69
   107.3  938.08   117.1  940.18   126.9   941.1   136.6  941.12     244  938.68
   263.5  938.54   273.2  938.67     283   939.2   292.8  940.21   312.3  943.01
   341.6  947.77   351.3  950.51   361.1  954.83   380.6  965.15   390.3  969.84
   400.1  973.83   409.9  977.22   429.4  982.86   439.1  985.93   448.9  989.98
#Mann= 3 , 0 , 0
       0      .1       0    88.7    .045       0   103.7     .06       0
Bank Sta=88.7,103.7
XS Rating Curve= 0 ,0
Exp/Cntr=0.3,0.1

Type RM Length L Ch R = 1 ,12706.6 ,123.2,123.7,124.3
XS GIS Cut Line= 2
     1654445.945      279023.343     1654231.443      279423.084
#Sta/Elev= 30
       0     990    19.3  979.97      29  974.67    57.9  958.51    67.6  953.19
    86.9  942.25    96.5   937.8   106.2   936.1   115.8  937.33   118.2  937.74
   125.5  938.99   135.1  939.25   154.4  938.44   173.7  938.06   202.7  938.14
   231.6   938.4   270.3  938.48   279.9   938.8   289.6  939.68   299.2  941.08
   328.2  945.71   337.8  947.44   347.5  950.05   357.1  953.88   366.8  958.41
   395.7  972.82     415  982.15   434.4  991.25     444  995.66   453.7  999.99
#Mann= 3 , 0 , 0
       0      .1       0    96.5    .045       0   118.2     .06       0
Bank Sta=96.5,118.2
XS Rating Curve= 0 ,0
Exp/Cntr=0.3,0.1

Type RM Length L Ch R = 1 ,12582.9 ,121.5,121.4,121.2
XS GIS Cut Line= 2
     1654365.862      278921.611     1654129.522      279335.114
#Sta/Elev= 28
       0 1014.46    58.3  987.53      68  982.28    77.8  976.14    87.5  968.97
    97.2  961.01   116.6  941.48   126.4  935.64   136.1  933.86   145.8  934.58
   156.3   936.1   165.2  937.08     175  937.52   213.8  937.92   262.4  938.24
   330.5  938.84   340.2  939.18   349.9  940.17   379.1  944.78   388.8  946.43
   398.5     949   408.2  953.24     418  958.62   437.4  970.02   447.1  975.13
   456.8  979.72   466.6  983.87   476.3  987.79
#Mann= 3 , 0 , 0
       0      .1       0   126.4    .045       0   156.3     .06       0
Bank Sta=126.4,156.3
XS Rating Curve= 0 ,0
Exp/Cntr=0.3,0.1

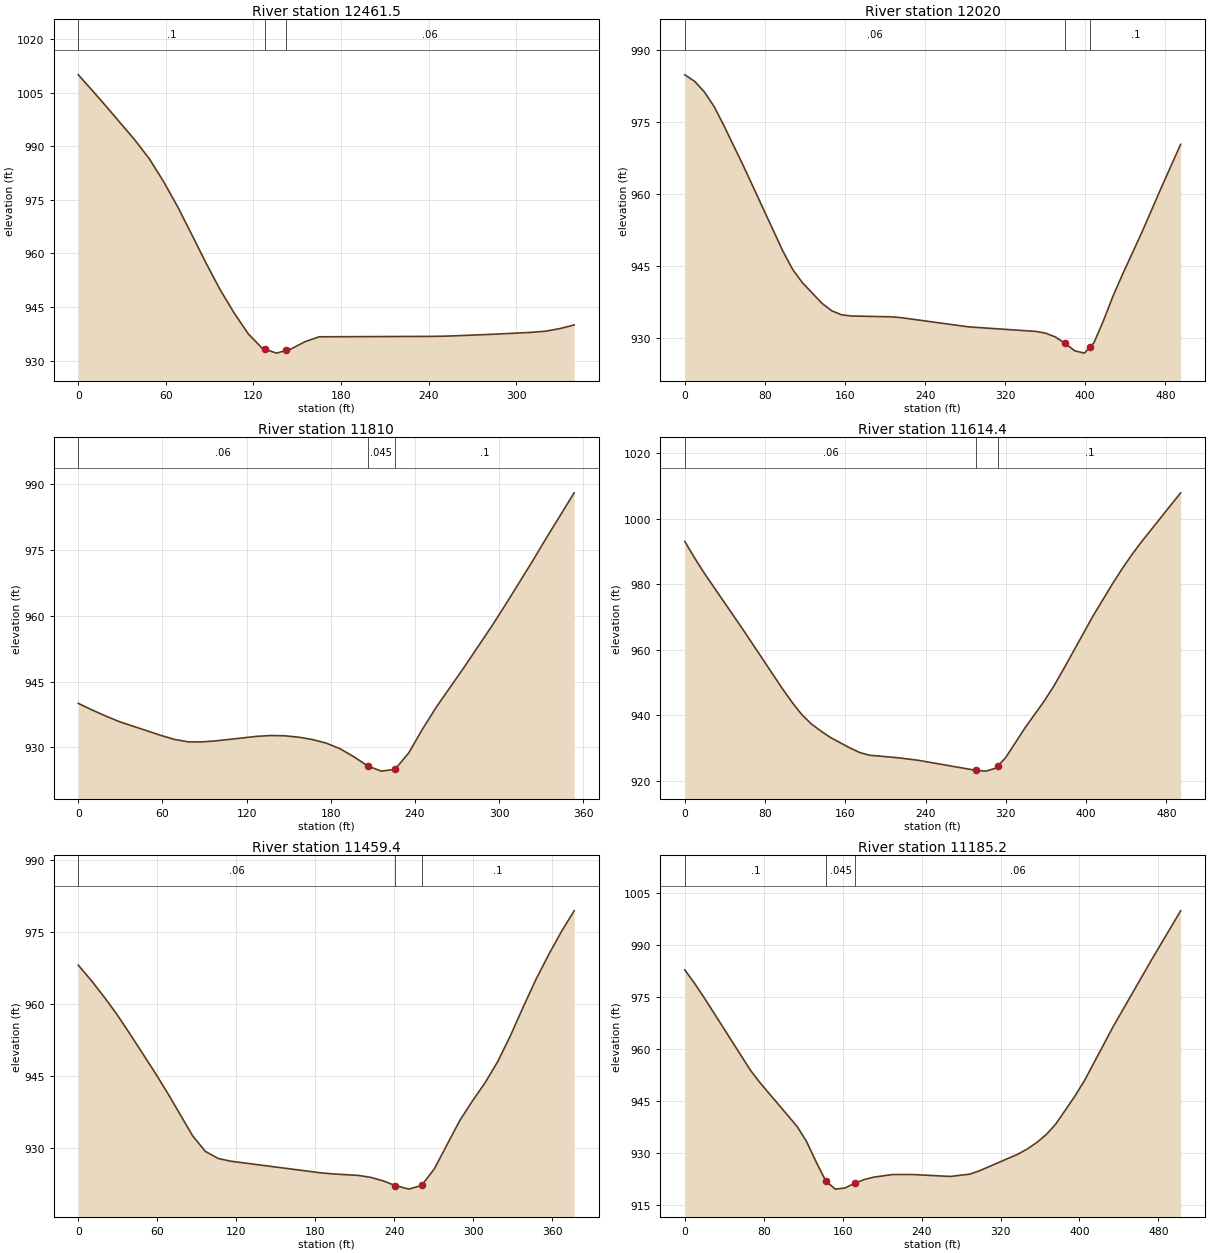
Type RM Length L Ch R = 1 ,12461.5 ,441.2,441.5,441.7
XS GIS Cut Line= 2
      1654264.37       278864.45     1654096.741       279160.03
#Sta/Elev= 26
       0    1010     9.7 1005.57    19.4 1001.02    38.8  991.74    48.5  986.59
    58.2  980.28      68  973.14    77.7  965.33    87.4   957.4    97.1  949.92
   106.8  943.33   116.5  937.49   126.2  933.39   127.6  933.21   135.9  932.11
   142.6  932.89   145.6  933.24   155.3   935.3     165  936.68   242.7   936.8
   252.4  936.87   281.6  937.34   310.7  937.93   320.4  938.26   330.1  938.98
   339.8     940
#Mann= 3 , 0 , 0
       0      .1       0   127.6    .045       0   142.6     .06       0
Bank Sta=127.6,142.6
XS Rating Curve= 0 ,0
Exp/Cntr=0.3,0.1

Type RM Length L Ch R = 1 ,12020   ,212.6,210,207.2
XS GIS Cut Line= 3
     1653979.901      278642.135     1653832.552      278861.723
     1653714.944      279060.358
#Sta/Elev= 30
       0  984.82     9.8  983.48    19.6  981.24    29.4  978.18    39.2  974.18
    58.8  965.72    97.9  948.11   107.7  944.28   117.5  941.49   137.1  937.18
   146.9  935.62   156.7   934.8   166.5  934.55   205.7  934.38   215.5  934.22
   283.7  932.28     351  931.33   360.6  930.96   370.2  930.18   379.9  928.83
   389.5   927.3   399.1  926.81   405.1  928.16   408.7  928.97   418.3  933.62
     428  938.82   437.6  943.37   456.8  952.08     476  961.31   495.3  970.33
#Mann= 3 , 0 , 0
       0     .06       0   379.9    .045       0   405.1      .1       0
Bank Sta=379.9,405.1
XS Rating Curve= 0 ,0
Exp/Cntr=0.3,0.1

Type RM Length L Ch R = 1 ,11810   ,196.2,195.6,194.9
XS GIS Cut Line= 2
      1653664.15      278691.167     1653522.147      279014.857
#Sta/Elev= 30
       0  940.02     9.8  938.51    19.6  937.12    29.5  935.82    58.9  932.71
    68.7  931.79    78.6  931.23    88.4  931.24    98.2  931.47   127.6  932.51
   137.5  932.69   147.3  932.62   157.1  932.31   166.9  931.77   176.7  930.96
   186.6  929.67   196.4  927.86   206.2  925.77     216  924.57   225.8  924.98
   235.6  928.74   245.5  934.21   255.3   939.2   274.9  948.18   294.6  957.54
   304.4  962.44   314.2  967.47     324  972.55   333.8  977.78   353.5  988.01
#Mann= 3 , 0 , 0
       0     .06       0   206.2    .045       0   225.8      .1       0
Bank Sta=206.2,225.8
XS Rating Curve= 0 ,0
Exp/Cntr=0.3,0.1

Type RM Length L Ch R = 1 ,11614.4 ,156,155,153.9
XS GIS Cut Line= 2
      1653510.37      278537.535     1653324.515      278995.536
#Sta/Elev= 30
       0  993.02     9.7  988.05    19.4  983.37    58.2  966.05    96.9  948.28
   106.6  944.08   116.3  940.29     126  937.36   135.7  935.14   145.4  933.16
   164.8  929.95   174.4  928.59   184.1  927.77   213.2  926.97   232.6  926.22
   290.8  923.12   300.4  922.91   310.1  923.83   312.5  924.61   319.8     927
   339.2  936.14   358.6  944.43   368.3  949.08     378  954.28     407   970.3
   426.4  980.12   436.1  984.73   445.8  989.04   455.5     993   494.3 1007.88
#Mann= 3 , 0 , 0
       0     .06       0   290.8    .045       0   312.5      .1       0
Bank Sta=290.8,312.5
XS Rating Curve= 0 ,0
Exp/Cntr=0.3,0.1

Type RM Length L Ch R = 1 ,11459.4 ,275.6,274.3,271.5
XS GIS Cut Line= 2
     1653332.494      278531.766     1653208.431      278887.558
#Sta/Elev= 30
       0  968.01     9.7  964.87    19.3   961.5      29   957.9    38.6  953.96
      58  945.76    67.6   941.5      87  932.44    96.6  929.23   106.3  927.77
   115.9   927.2   183.6   924.8   193.2  924.56   212.6  924.25   222.2  923.84
   231.9  923.08     241  922.12   251.2  921.39   260.9  922.16   270.5  925.59
   289.8  935.63   299.5  939.74   309.2  943.58   318.8  947.98   328.5   953.4
   338.2  959.38   347.8  965.06   357.5  970.23   367.1  974.99   376.8  979.32
#Mann= 3 , 0 , 0
       0     .06       0     241    .045       0   260.9      .1       0
Bank Sta=241,260.9
XS Rating Curve= 0 ,0
Exp/Cntr=0.3,0.1

Type RM Length L Ch R = 1 ,11185.2 ,144.9,141.6,138.2
XS GIS Cut Line= 4
     1653174.677      278428.858     1653130.236      278543.919
     1653071.915      278749.773     1653063.234      278914.704
#Sta/Elev= 30
       0  982.83     9.5  979.14      19  975.11    66.4  953.95    75.9  950.41
   113.9  937.65   123.3  933.38   133.1  927.47   142.8  921.99   143.5  921.82
   152.5   919.6   162.2  919.92     172  921.26   181.7  922.36   191.4  923.05
   210.9  923.82   230.3  923.82   269.2  923.26   288.7  923.92   298.4  924.86
   337.3  929.65     347  931.16   356.7  933.04   366.4  935.36   376.2  938.46
   395.6  946.53   405.3  951.03   434.4  966.62   473.3  985.87   502.5  999.88
#Mann= 3 , 0 , 0
       0      .1       0   143.5    .045       0     172     .06       0
Bank Sta=143.5,172
XS Rating Curve= 0 ,0
Exp/Cntr=0.3,0.1