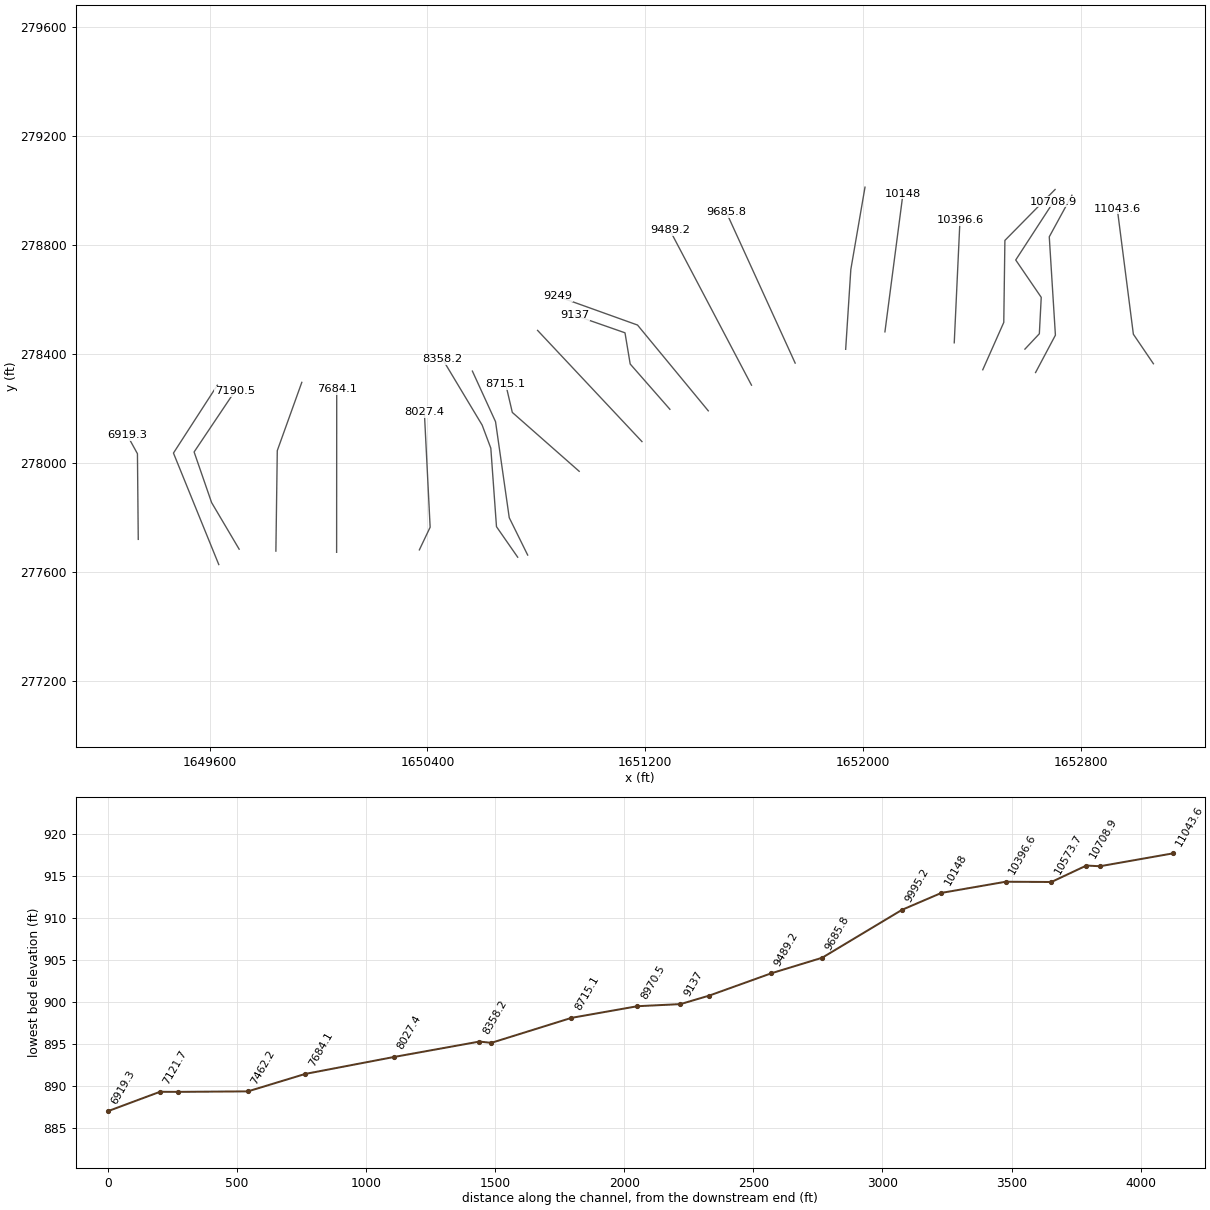
HEC-RAS study BFLCLFFRK.prj: BFLCLFFRK

--- BFLCLFFRK.g01 (geometry) --- (continued)

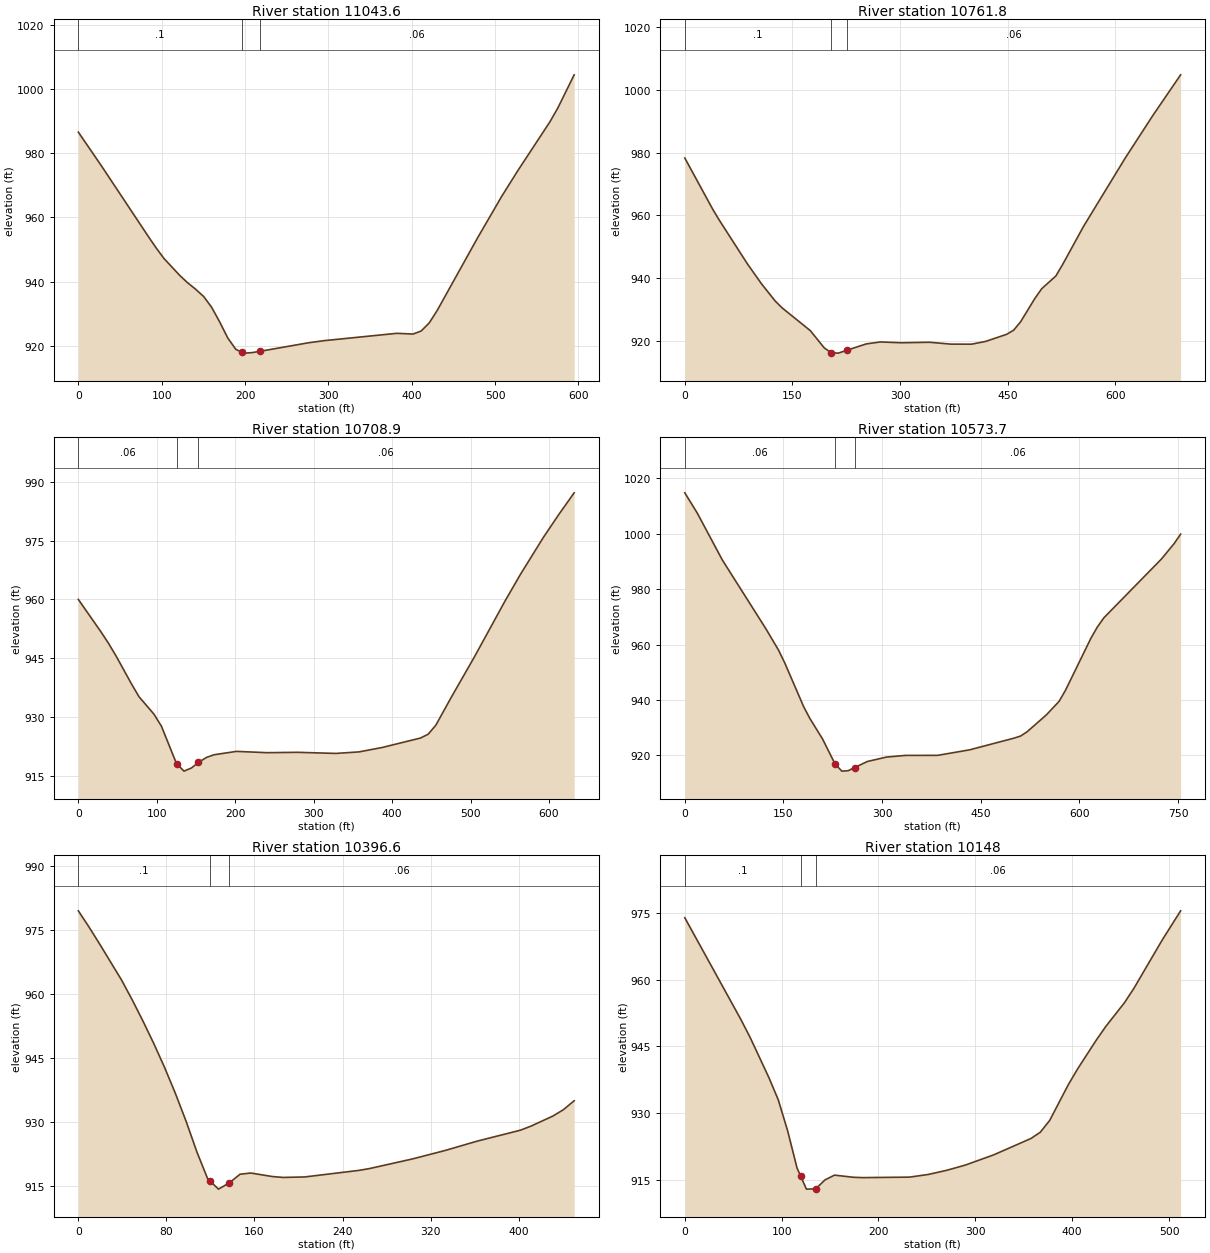
Type RM Length L Ch R = 1 ,11043.6 ,283.2,281.8,280.3
XS GIS Cut Line= 3
     1653067.422      278363.623      1652993.79      278471.996
     1652934.762      278932.065
#Sta/Elev= 30
       0  986.57    28.1  975.91    84.2  953.97    93.6  950.41   102.9  947.16
   121.7  941.92     131  939.66   140.7  937.63   150.4  935.35     160  931.97
   169.7  927.39   179.3  922.43     189  918.88   196.2  918.01   198.7  917.71
   208.3  917.86     218  918.28     276  920.93   295.3  921.61   382.3  923.88
   401.6  923.65   411.3   924.6   420.9  927.08   430.6  931.01   478.9  953.57
   507.9  966.52   527.2  974.52   565.9  989.81   575.5  994.18   594.9 1004.42
#Mann= 3 , 0 , 0
       0      .1       0   196.2    .045       0     218     .06       0
Bank Sta=196.2,218
XS Rating Curve= 0 ,0
Exp/Cntr=0.3,0.1

Type RM Length L Ch R = 1 ,10761.8 ,55.4,52.9,50.3
XS GIS Cut Line= 4
     1652634.415      278331.371     1652707.332      278468.523
     1652684.762      278829.635     1652768.095      278982.412
#Sta/Elev= 30
       0   978.3    38.8  962.04    48.5  958.36    87.4  944.56   106.8  938.29
   126.2  932.72   135.9  930.54   174.9  923.36   194.4  917.85   204.2  916.29
     214  916.18   225.7  917.08   253.1  919.12   272.7  919.74     302  919.48
   341.1  919.64   370.5  919.05   399.8  919.03   419.4  919.91   448.7  922.17
   458.5   923.5   468.2  926.17   487.8  933.51   497.6   936.7   517.2  940.72
   526.8  944.42   555.8   956.5   613.8  978.22   652.5  991.84   691.2 1004.78
#Mann= 3 , 0 , 0
       0      .1       0   204.2    .045       0   225.7     .06       0
Bank Sta=204.2,225.7
XS Rating Curve= 0 ,0
Exp/Cntr=0.3,0.1

Type RM Length L Ch R = 1 ,10708.9 ,134.4,135.2,136
XS GIS Cut Line= 5
     1652595.365      278417.338     1652648.304      278473.732
     1652655.248      278607.412     1652561.498      278744.565
     1652700.387      278958.107
#Sta/Elev= 30
       0     960      29   951.7    38.7  948.74    48.3  945.53    67.7   938.5
    77.4   935.2    96.5  930.75     106  927.68   125.2  918.15   134.7  916.26
   144.3  917.07     153  918.47   163.4  919.75     173  920.43   201.6  921.29
   240.5  920.96   279.6  921.05   328.5  920.77   357.8  921.16   387.1  922.27
   436.1  924.68   445.9  925.65   455.7  927.94   475.3  935.01   504.7  945.27
   543.9  959.56   563.5  966.34   592.9  975.81   612.5  981.63   632.1  987.15
#Mann= 3 , 0 , 0
       0     .06       0   125.2    .045       0     153     .06       0
Bank Sta=125.2,153
XS Rating Curve= 0 ,0
Exp/Cntr=0.3,0.1

Type RM Length L Ch R = 1 ,10573.7 ,177.8,177.1,176.3
XS GIS Cut Line= 4
      1652440.42      278341.525     1652517.602      278515.387
     1652521.729      278816.375     1652706.164      279003.416
#Sta/Elev= 30
       0 1014.75      19 1007.43    57.1   990.5   123.6  965.57   142.7  957.91
   152.2  953.24   180.7  937.58   190.2   933.3   209.6  925.85   228.5  916.85
   238.8   914.3   248.5  914.45   258.2  915.58   277.6  917.78   306.8  919.38
   335.9  919.98   384.4  919.99     433  921.98     501  926.23   510.7  926.98
   520.4  928.49   549.6  934.56   569.1  939.48   578.8  943.46   617.7  962.36
   627.4  966.35   637.2  969.64   724.7  990.85   744.2  996.48   753.9  999.85
#Mann= 3 , 0 , 0
       0     .06       0   228.5    .045       0   258.2     .06       0
Bank Sta=228.5,258.2
XS Rating Curve= 0 ,0
Exp/Cntr=0.3,0.1

Type RM Length L Ch R = 1 ,10396.6 ,250.5,248.6,246.7
XS GIS Cut Line= 2
     1652335.599      278440.502     1652356.637      278890.398
#Sta/Elev= 30
       0  979.52     9.8  975.69    19.6  971.65    39.2  963.34      49  958.64
    58.8  953.65    68.5  948.46    78.3  942.86    88.1   936.8    97.9  930.23
   107.7  923.04   117.5  916.75   119.7  916.21   127.3  914.33   137.1  915.78
   146.9  917.82   156.7   918.1   176.2  917.28     186  917.07   205.6  917.18
   254.6  918.71   264.4  919.14   303.5   921.4   332.9  923.36   362.3  925.57
   401.4  928.12   411.2  929.09   430.8  931.41   440.6  932.93   450.4  935.03
#Mann= 3 , 0 , 0
       0      .1       0   119.7    .045       0   137.1     .06       0
Bank Sta=119.7,137.1
XS Rating Curve= 0 ,0
Exp/Cntr=0.3,0.1

Type RM Length L Ch R = 1 ,10148   ,151.4,152.8,154.1
XS GIS Cut Line= 2
     1652080.885      278480.694     1652147.281      278988.387
#Sta/Elev= 30
       0  973.86      58  951.01    67.6  946.96      87  937.94    96.6  932.98
   106.3     926   115.9  917.74   119.5  915.98   125.6     913   135.2  913.07
   144.9  915.09   154.6  916.14   173.9  915.66   183.6  915.58   231.9  915.69
   251.2  916.28   270.5  917.22   289.8   918.4   318.8  920.67   357.4  924.35
   367.1  925.76   376.8  928.41   396.1  936.45   405.8  940.02   425.1  946.48
   434.7  949.47     454   954.8   463.7  958.01   492.7  968.76     512  975.41
#Mann= 3 , 0 , 0
       0      .1       0   119.5    .045       0   135.2     .06       0
Bank Sta=119.5,135.2
XS Rating Curve= 0 ,0
Exp/Cntr=0.3,0.1

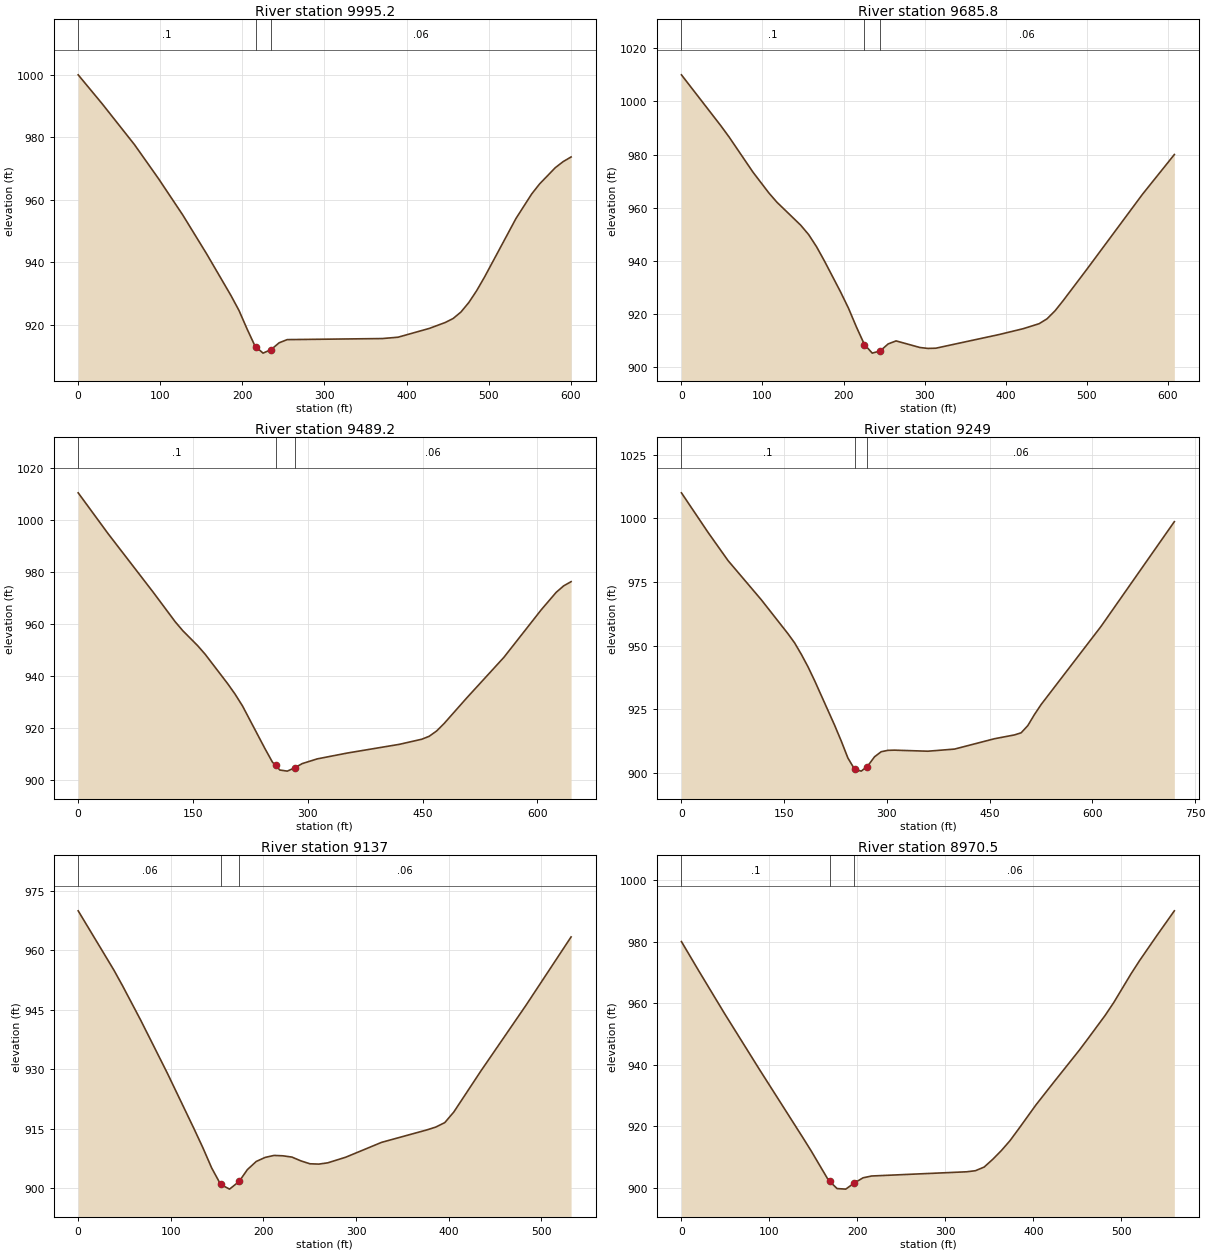
Type RM Length L Ch R = 1 ,9995.2  ,297.8,309.4,321.1
XS GIS Cut Line= 3
     1651936.615      278416.648     1651955.595      278709.843
     1652007.679      279011.926
#Sta/Elev= 30
       0    1000    29.4  990.68    68.6  977.66    97.9  966.77   127.3   955.2
   156.7  942.63   186.1   929.4   195.9  924.61   205.7  918.72   215.5  913.18
   216.5  912.95   225.2  910.98     235  912.12   244.8  914.29   254.6   915.3
   370.4  915.64   389.6  916.07   427.9   918.9   447.1  920.78   456.7  922.05
   466.2  924.12   475.8  927.16   485.4  930.97     495  935.33   533.3  954.06
   552.4  961.89     562  965.09   581.2  970.31   590.8  972.25   600.4  973.73
#Mann= 3 , 0 , 0
       0      .1       0   216.5    .045       0     235     .06       0
Bank Sta=216.5,235
XS Rating Curve= 0 ,0
Exp/Cntr=0.3,0.1

Type RM Length L Ch R = 1 ,9685.8  ,195.3,196.6,197.9
XS GIS Cut Line= 2
     1651751.031      278366.014     1651498.351      278919.092
#Sta/Elev= 30
       0    1010      49  990.68    58.8   986.6    88.3  973.35   107.9  965.53
   117.7  962.09   147.1  953.42   156.9  949.89   166.7   945.3   176.5  939.89
   196.2  928.36     206  922.23   215.8  915.15   225.8  908.47   235.4  905.26
   245.2  906.09     255  908.72   264.8  909.86   294.2  907.38     304  907.03
   313.8  907.11   392.3  912.28   421.7  914.46   441.3  916.34   451.1  918.19
     461  921.22   470.8  924.97   500.2  936.82   568.8  965.05   608.1     980
#Mann= 3 , 0 , 0
       0      .1       0   225.8    .045       0   245.2     .06       0
Bank Sta=225.8,245.2
XS Rating Curve= 0 ,0
Exp/Cntr=0.3,0.1

Type RM Length L Ch R = 1 ,9489.2  ,235.7,240.2,245.1
XS GIS Cut Line= 2
     1651590.571      278284.894     1651290.307      278854.648
#Sta/Elev= 30
       0  1010.3      39  994.64    97.6  972.28   126.9  960.73   136.6  957.37
   156.1   951.6   165.9   948.3   195.2  937.04   204.9  933.02   214.7  928.44
     244  912.07   253.7  906.92   257.9   905.6   263.5  903.83   273.2  903.41
     283   904.7   292.7   906.3   312.3  908.11   351.3  910.34   419.6   913.7
   448.9  915.66   458.6  916.79   468.4  918.85   478.2  921.73   507.4  931.44
   556.2  947.11     605  965.38   624.5  972.07   634.3  974.57     644  976.18
#Mann= 3 , 0 , 0
       0      .1       0   257.9    .045       0     283     .06       0
Bank Sta=257.9,283
XS Rating Curve= 0 ,0
Exp/Cntr=0.3,0.1

Type RM Length L Ch R = 1 ,9249    ,111.2,112,112.2
XS GIS Cut Line= 3
     1651431.752      278190.754     1651171.725      278505.711
     1650878.667      278610.742
#Sta/Elev= 30
       0    1010    38.9  994.45    68.1  983.38   116.7  967.99   155.6  954.67
   165.3  951.07     175  946.62   184.8   941.7   194.5  936.24   223.7  918.74
   233.4  912.53   243.1  905.87   252.8  901.51   262.6  900.75   270.3  902.44
   272.3  902.88     282  906.39   291.7  908.37   301.5  908.91   311.2  908.98
   359.8  908.57   398.7   909.4   457.1  913.47   486.2  914.96     496  915.79
   505.7   918.6   515.4  922.95   525.2   926.9   612.7  957.58   719.7  998.68
#Mann= 3 , 0 , 0
       0      .1       0   252.8    .045       0   270.3     .06       0
Bank Sta=252.8,270.3
XS Rating Curve= 0 ,0
Exp/Cntr=0.3,0.1

Type RM Length L Ch R = 1 ,9137    ,165.6,166.5,167.4
XS GIS Cut Line= 4
     1651290.713      278196.419     1651144.832      278362.621
     1651125.734      278477.204     1650941.707       278541.44
#Sta/Elev= 30
       0     970    38.5  955.06    48.1  950.99    67.3  942.48    96.2  929.04
     125  915.01   134.6   910.2   144.2  905.04   153.8  900.92   163.4  899.73
   173.8  901.67   182.7  904.66   192.3  906.72   201.9  907.74   211.5  908.24
   221.1  908.14   230.8  907.82   240.5  906.86   250.2  906.13   259.9  906.05
   269.5  906.37   288.9  907.79   327.6  911.54   376.3  914.67     386  915.39
   395.8  916.52   405.5  919.18   434.8  929.56   483.5  946.15   532.2  963.41
#Mann= 3 , 0 , 0
       0     .06       0   153.8    .045       0   173.8     .06       0
Bank Sta=153.8,173.8
XS Rating Curve= 0 ,0
Exp/Cntr=0.3,0.1

Type RM Length L Ch R = 1 ,8970.5  ,253.2,255.4,257.6
XS GIS Cut Line= 2
     1651188.111      278077.782     1650804.555      278486.026
#Sta/Elev= 30
       0     980    19.6  970.52    49.1  956.54    88.4  938.52   137.6  916.41
   147.4  911.93   167.1  902.38   168.5  901.99   176.9  899.66   186.7  899.48
   196.6  901.49   206.4  903.16   216.2  903.75   324.3  905.12   334.1  905.47
     344  906.65   353.8  909.17   363.6  912.02   373.4  915.24   383.3  919.08
   402.9  926.87   422.6  934.05   452.1  944.64   461.9  948.37   481.5  955.97
   491.4   960.2     511  969.52   520.8  973.86   540.5  982.03   560.2     990
#Mann= 3 , 0 , 0
       0      .1       0   168.5    .045       0   196.6     .06       0
Bank Sta=168.5,196.6
XS Rating Curve= 0 ,0
Exp/Cntr=0.3,0.1

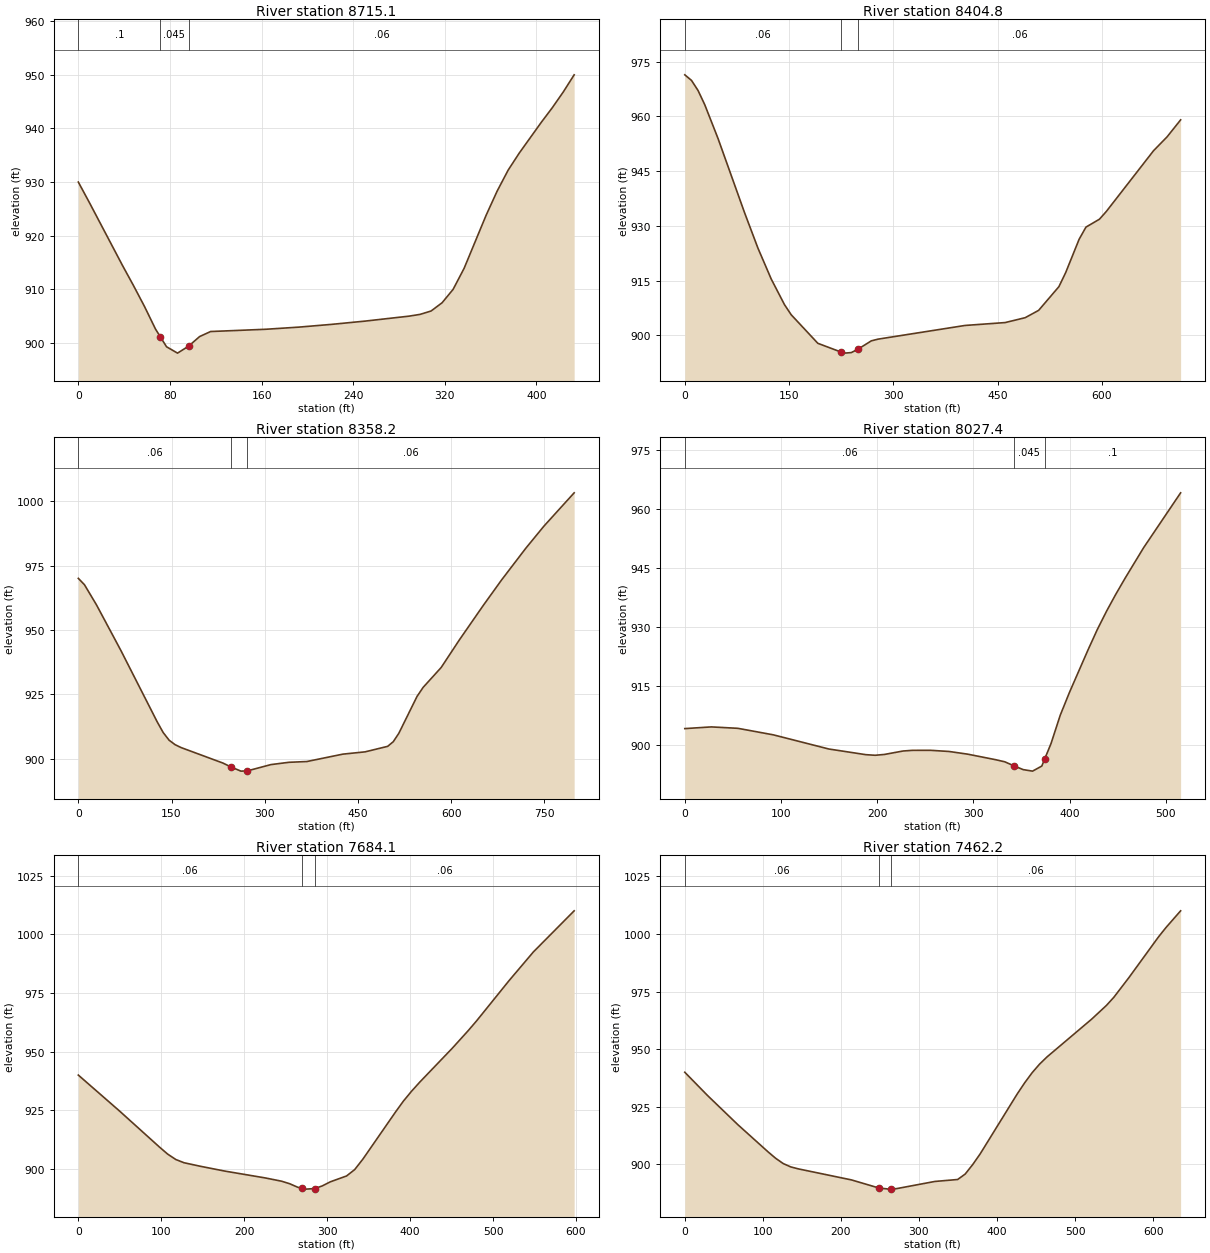
Type RM Length L Ch R = 1 ,8715.1  ,308.7,310.3,298.1
XS GIS Cut Line= 3
     1650957.372      277968.743     1650711.682      278184.906
     1650687.584      278287.743
#Sta/Elev= 30
       0     930     9.6   926.2    38.5  914.47    48.1  910.72    57.8  906.78
    67.4  902.57    71.6  901.13      77  899.28    86.6  898.09    96.2  899.38
   105.9  901.18   115.5  902.12   163.6  902.54   192.5  902.94   221.4  903.46
   250.2  904.06   288.8  904.99   298.4  905.32     308  905.95   317.6  907.49
   327.2  909.98   336.8   913.9     356  923.79   365.6  928.29   375.3  932.24
   384.9  935.39   404.1  941.12   413.7  943.84   423.3  946.78   432.9  950.01
#Mann= 3 , 0 , 0
       0      .1       0    71.6    .045       0    96.2     .06       0
Bank Sta=71.6,96.2
XS Rating Curve= 0 ,0
Exp/Cntr=0.3,0.1

Type RM Length L Ch R = 1 ,8404.8  ,64.2,46.6,41.7
XS GIS Cut Line= 4
     1650768.095      277661.232     1650700.387      277798.385
      1650650.04      278150.815      1650564.97      278336.579
#Sta/Elev= 30
       0  971.36     9.6  969.84    19.1  967.06    28.7  963.18    47.8  953.92
      86  933.58   105.2  923.89   124.3  915.43   143.4   908.4     153  905.64
   191.4   897.8   225.1  895.38   229.9  895.11   239.6  895.26   249.2   896.2
   268.4  898.48     278  898.94   403.1  902.69   460.8  903.48   489.7  904.82
     509  906.82   538.2  913.32   547.9  917.15   567.3  926.31   577.1  929.63
   596.5   931.8   606.3   933.9   674.4  950.58   693.8  954.36   713.3  959.02
#Mann= 3 , 0 , 0
       0     .06       0   225.1    .045       0   249.2     .06       0
Bank Sta=225.1,249.2
XS Rating Curve= 0 ,0
Exp/Cntr=0.3,0.1

Type RM Length L Ch R = 1 ,8358.2  ,332.6,330.8,329.1
XS GIS Cut Line= 5
     1650731.458      277653.324     1650653.512      277765.398
     1650632.679      278053.593     1650600.897      278138.212
     1650455.595      278379.982
#Sta/Elev= 30
       0  970.02     9.8  967.57    29.2  959.75    68.3  942.13   126.8  914.43
   136.5  910.24   146.2  907.23   155.8  905.51   165.4  904.39   232.8  898.38
   245.7  896.86   261.7  895.26   271.4  895.32   309.9  897.79   338.8  898.68
   367.7  898.98   425.5  901.84   461.6  902.74   497.8  904.87   506.8  906.67
   515.8  909.95     545   924.2   554.8  927.72   583.9  935.45   613.1  946.12
     652  959.64   681.2  969.43   720.1   981.7   749.3  990.28   797.9 1003.19
#Mann= 3 , 0 , 0
       0     .06       0   245.7    .045       0   271.4     .06       0
Bank Sta=245.7,271.4
XS Rating Curve= 0 ,0
Exp/Cntr=0.3,0.1

Type RM Length L Ch R = 1 ,8027.4  ,344.9,343.3,341.3
XS GIS Cut Line= 3
     1650370.121      277680.282     1650409.719      277763.415
      1650388.45      278186.183
#Sta/Elev= 30
       0  904.23    27.6  904.66    55.2   904.3    92.1  902.64   149.8  899.04
   188.3   897.6   197.9  897.45   207.5  897.66   226.8  898.53   236.4   898.7
   255.6  898.71   274.9  898.41   294.1  897.73     323  896.33   332.6  895.79
   342.2  894.76   351.8   893.8   361.5  893.42   371.1  894.71     374  896.44
   380.7  900.44   390.3  907.65   399.9  913.46   419.2  924.26   428.8  929.41
   438.4  934.07     448  938.37   457.7  942.46   476.9   950.2   515.4  964.16
#Mann= 3 , 0 , 0
       0     .06       0   342.2    .045       0     374      .1       0
Bank Sta=342.2,374
XS Rating Curve= 0 ,0
Exp/Cntr=0.3,0.1

Type RM Length L Ch R = 1 ,7684.1  ,221.4,222,222.4
XS GIS Cut Line= 2
     1650066.077      277671.331     1650066.446      278269.125
#Sta/Elev= 30
       0     940      49   924.9      98  909.27   107.8   906.3   117.6  904.01
   127.4  902.65     147  901.15   176.4   899.1   225.4  896.17     245  894.78
   254.8   893.7   264.6  892.19   269.9  891.76   274.4   891.4   284.9  891.64
     294  892.75   303.8  894.51   323.4  897.01   333.2  899.73     343  904.15
   382.2  924.15     392  928.94   401.8  933.14   411.6  936.98   450.8  951.42
   470.4  959.07   480.2  963.12   519.4  980.29   548.8  992.54   597.8    1010
#Mann= 3 , 0 , 0
       0     .06       0   269.9    .045       0   284.9     .06       0
Bank Sta=269.9,284.9
XS Rating Curve= 0 ,0
Exp/Cntr=0.3,0.1

Type RM Length L Ch R = 1 ,7462.2  ,263.8,271.6,279.5
XS GIS Cut Line= 3
     1649842.894      277675.758     1649848.036      278044.627
     1649938.126       278295.26
#Sta/Elev= 30
       0     940    29.1  929.93      68  917.26   106.8  905.44   116.5  902.67
   126.2  900.38   135.9  898.94   145.6  898.09   213.6  893.31   248.7   889.8
   262.1  889.32   263.7  889.36   271.8  889.56   320.4  892.65   349.5  893.49
   359.2  895.85   368.9     900   378.4   904.6     426  930.66   435.5  935.46
     445  939.81   454.5  943.52     464  946.64   521.1  962.99   540.1  968.96
   549.6  972.49   568.6  980.88   606.7  998.62   616.2 1002.65   635.2    1010
#Mann= 3 , 0 , 0
       0     .06       0   248.7    .045       0   263.7     .06       0
Bank Sta=248.7,263.7
XS Rating Curve= 0 ,0
Exp/Cntr=0.3,0.1

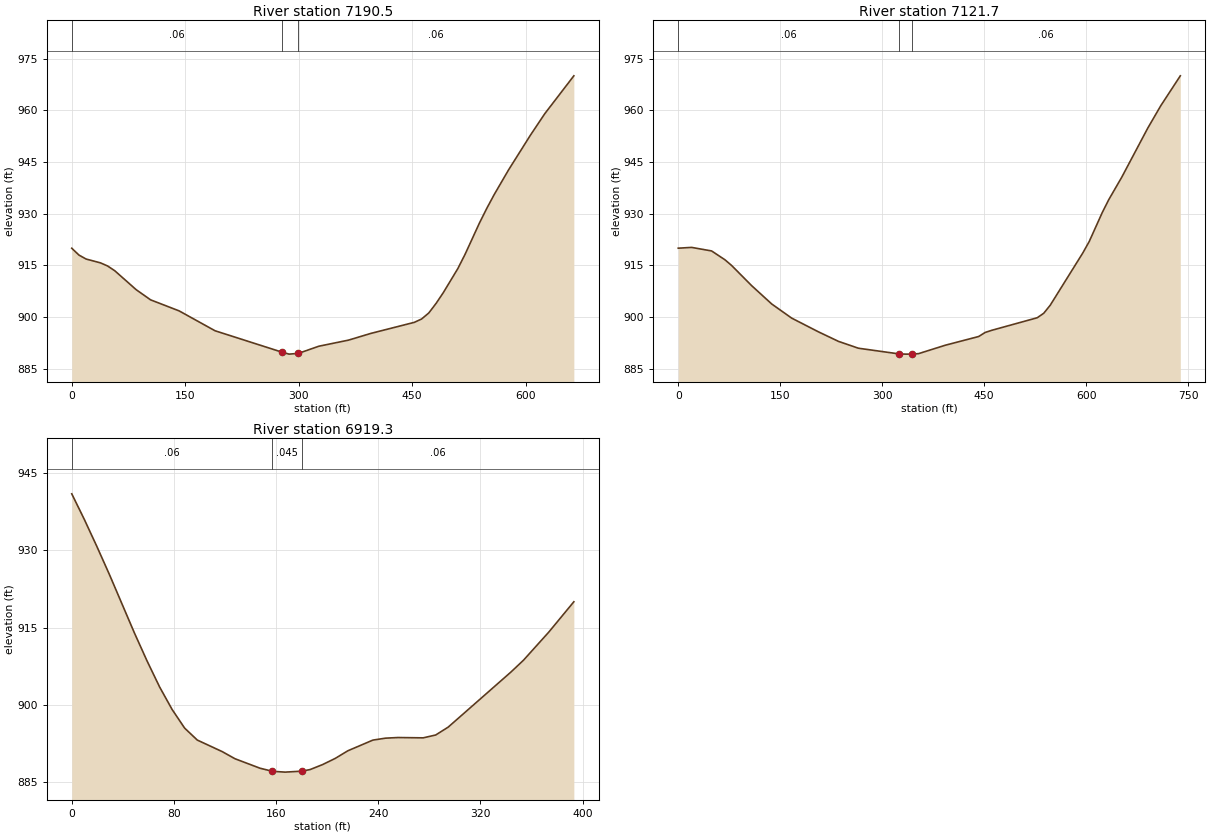
Type RM Length L Ch R = 1 ,7190.5  ,67.3,68.8,70.2
XS GIS Cut Line= 4
     1649707.883      277682.817     1649606.637       277853.94
     1649542.401      278039.704     1649692.066      278262.516
#Sta/Elev= 30
       0  919.98     9.5     918    18.9  916.85    37.9  915.74    47.3  914.84
    56.8  913.46    85.2  907.95   104.2  905.01     142   901.8   189.4  896.04
   277.4  889.87   287.3  889.26   299.6  889.47   326.6  891.55   365.9  893.32
   395.4  895.27   452.9  898.48   462.5  899.45   472.1  901.22   481.7  903.99
   491.2  907.09   510.4  914.07     520  918.22   539.2  927.39   548.8  931.59
   558.4  935.51   577.5  942.71   606.3  952.75   625.4  959.02   663.8     970
#Mann= 3 , 0 , 0
       0     .06       0   277.4    .045       0   299.6     .06       0
Bank Sta=277.4,299.6
XS Rating Curve= 0 ,0
Exp/Cntr=0.3,0.1

Type RM Length L Ch R = 1 ,7121.7  ,219.7,202.4,183.7
XS GIS Cut Line= 3
     1649633.012      277626.362     1649466.507      278035.659
     1649627.651      278284.696
#Sta/Elev= 30
       0     920    19.6  920.23    49.1   919.2    68.7  916.64    78.6  914.97
     108  909.13   137.5  903.82   166.9  899.71   206.2  895.74   235.7  892.97
   265.1  890.98   324.2  889.35   333.9  889.27   343.7  889.27   353.5  889.41
   392.8  891.85   441.9  894.38   451.4  895.55     461  896.17     528  899.82
   537.6  901.12   547.1  903.44     595  918.59   604.5  921.93   623.7  930.34
   633.2  934.06   652.4   940.6   690.6  954.82   709.8  961.34   738.5     970
#Mann= 3 , 0 , 0
       0     .06       0   324.2    .045       0   343.7     .06       0
Bank Sta=324.2,343.7
XS Rating Curve= 0 ,0
Exp/Cntr=0.3,0.1

Type RM Length L Ch R = 1 ,6919.3  ,291.8,300.5,310.5
XS GIS Cut Line= 3
     1649337.167      277718.819     1649334.181      278033.276
     1649296.193      278102.173
#Sta/Elev= 30
       0  940.94     9.8  935.99    19.6  930.76    29.5  925.28    49.1  913.93
      59   908.5    68.8  903.47    78.6   899.1    88.4  895.49    98.3  893.17
   117.9  890.92   127.8  889.55   147.4  887.71   157.2  887.11   167.1  886.95
   180.2  887.14   186.7  887.45   196.5  888.42   206.4  889.62   216.2  891.09
   235.8  893.16   245.7  893.54   255.5  893.66   275.2   893.6     285  894.15
   294.8  895.68     344  906.38   353.8  908.67   373.5  914.09   393.2     920
#Mann= 3 , 0 , 0
       0     .06       0   157.2    .045       0   180.2     .06       0
Bank Sta=157.2,180.2
XS Rating Curve= 0 ,0
Exp/Cntr=0.3,0.1