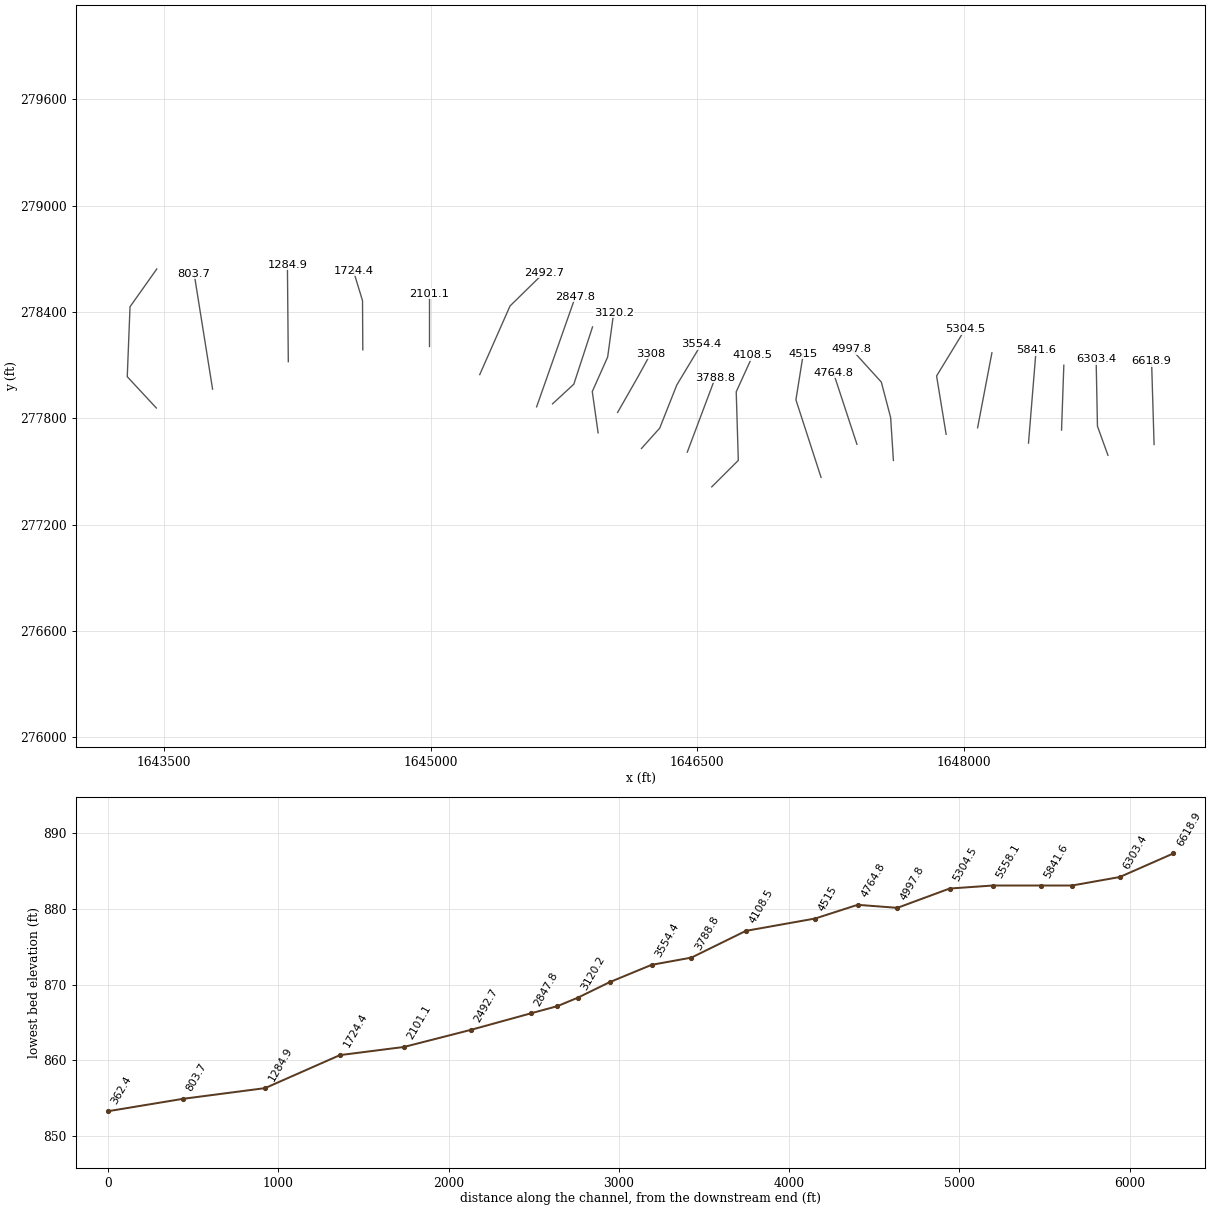
HEC-RAS study BFLCLFFRK.prj: BFLCLFFRK

--- BFLCLFFRK.g01 (geometry) --- (continued)

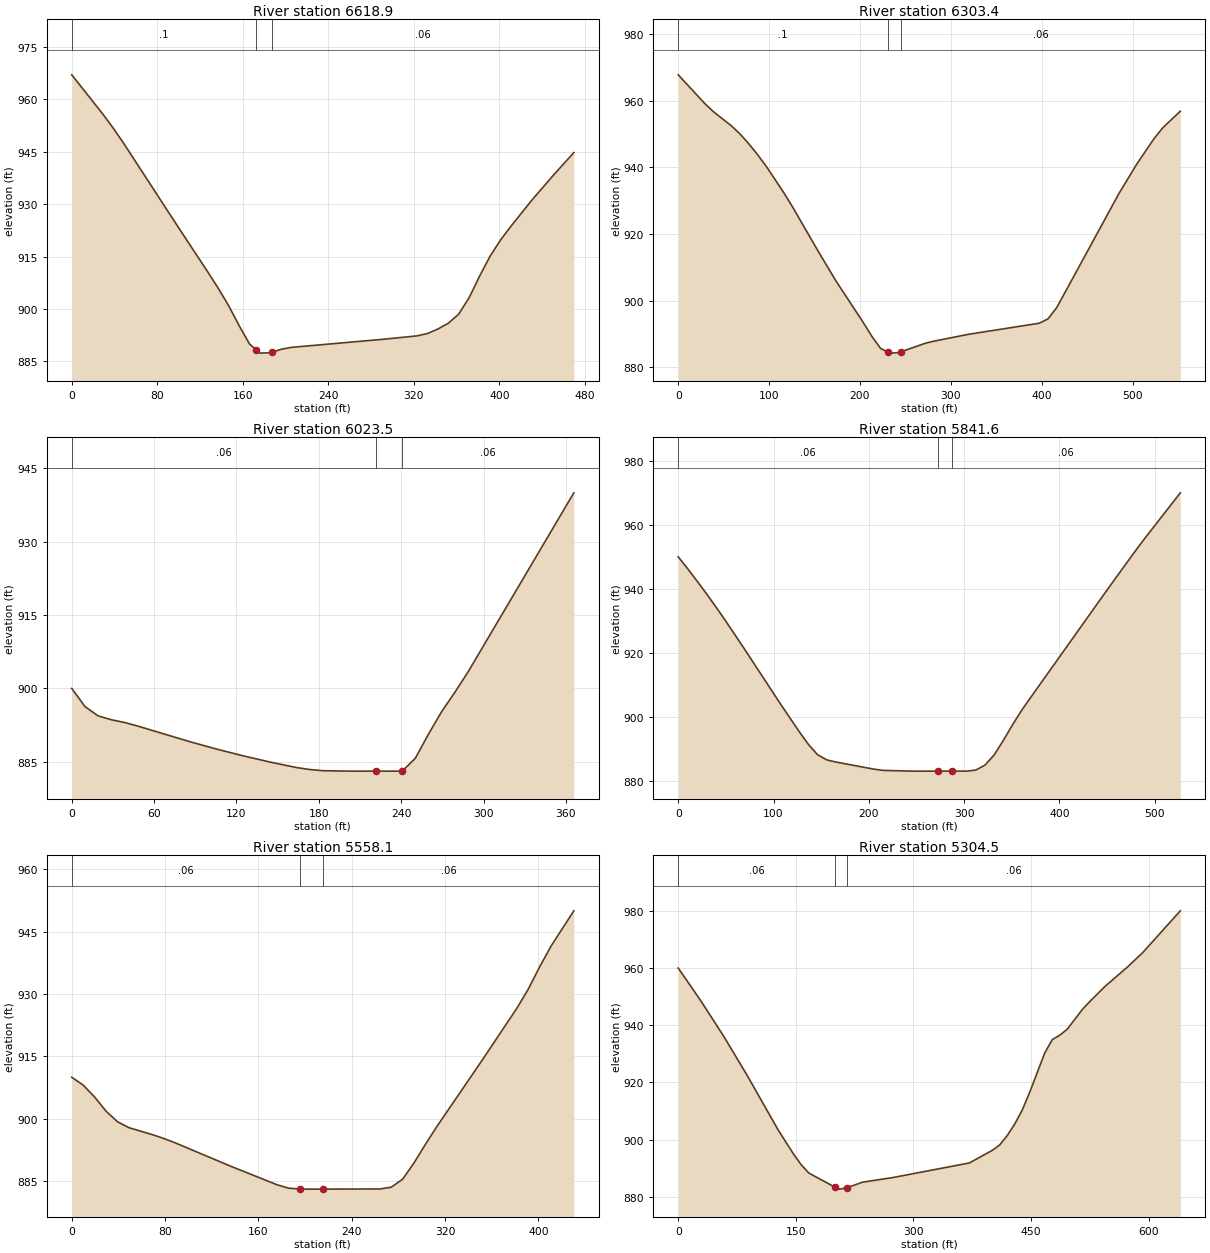
Type RM Length L Ch R = 1 ,6618.9  ,315.7,315.4,315.1
XS GIS Cut Line= 2
     1649071.042      277652.282     1649056.971      278121.749
#Sta/Elev= 30
       0  967.02    29.4  955.65    39.1  951.63    48.9  947.25    97.8  924.25
   127.2  910.61     137  905.93   146.8   900.9   156.6   895.2   166.3  889.95
   172.4  888.33   176.1  887.34   185.9  887.45   187.4   887.6   195.7  888.42
   205.5  888.99   293.6  891.37   322.9  892.28   332.7  892.94   342.5  894.24
   352.3  895.91     362   898.5   371.8  903.26   381.6  909.42   391.4  915.13
   401.2  919.76     411  923.73   430.5  931.17   450.1  938.11   469.7  944.76
#Mann= 3 , 0 , 0
       0      .1       0   172.4    .045       0   187.4     .06       0
Bank Sta=172.4,187.4
XS Rating Curve= 0 ,0
Exp/Cntr=0.3,0.1

Type RM Length L Ch R = 1 ,6303.4  ,280.2,280,279
XS GIS Cut Line= 3
     1648811.472      277591.325     1648752.417      277755.147
     1648744.912      278133.476
#Sta/Elev= 30
       0  967.84      29  959.27    38.7  956.77      58  952.63    67.7  950.16
    77.4  947.21    87.1  943.93    96.7  940.42   116.1  932.46   125.8  928.15
   154.8  914.47   174.1  905.68   203.2  893.61     213   889.3   222.6  885.66
   230.3  884.53   232.4  884.22   242.1  884.35   245.3  884.64   271.2  887.12
   280.9  887.79   319.7  889.89   397.3   893.2     407  894.54   416.7  897.98
   484.6  931.99     504  940.77   523.4   948.6   533.1   951.9   552.5  956.91
#Mann= 3 , 0 , 0
       0      .1       0   230.3    .045       0   245.3     .06       0
Bank Sta=230.3,245.3
XS Rating Curve= 0 ,0
Exp/Cntr=0.3,0.1

Type RM Length L Ch R = 1 ,6023.5  ,182.9,181.9,180.5
XS GIS Cut Line= 2
     1648550.348      277733.626     1648563.161      278099.202
#Sta/Elev= 23
       0     900     9.6  896.31    19.2  894.39    28.9   893.6    38.5  893.04
    48.1  892.31    86.6  889.07   105.9  887.58   125.1  886.21   144.4  884.96
   163.6  883.84   173.3  883.43   182.9  883.19   202.2   883.1   221.4   883.1
   240.3   883.1   240.7   883.1   250.3  885.72   259.9  890.66   269.5  895.26
   279.2  899.25   288.8  903.41   365.8  939.99
#Mann= 3 , 0 , 0
       0     .06       0   221.4    .045       0   240.3     .06       0
Bank Sta=221.4,240.3
XS Rating Curve= 0 ,0
Exp/Cntr=0.3,0.1

Type RM Length L Ch R = 1 ,5841.6  ,283.5,283.4,280.4
XS GIS Cut Line= 2
     1648364.342      277660.264     1648407.084      278185.284
#Sta/Elev= 30
       0     950     9.8  946.34    19.5  942.55    29.3  938.64      39   934.6
    48.8  930.42    68.3  921.77   107.3  904.07   126.8  895.49   136.6  891.43
   146.3   888.2   156.1  886.58   165.8  885.92   204.8  883.74   214.6  883.34
   243.9   883.1   272.5   883.1   287.5   883.1   302.4   883.1   312.2  883.42
   321.9  884.98   331.7  888.24   341.4  892.82   351.2  897.78   360.9  902.34
   370.7  906.49   448.7  939.13     478   951.2   487.7  955.07   526.8     970
#Mann= 3 , 0 , 0
       0     .06       0   272.5    .045       0   287.5     .06       0
Bank Sta=272.5,287.5
XS Rating Curve= 0 ,0
Exp/Cntr=0.3,0.1

Type RM Length L Ch R = 1 ,5558.1  ,246,253.6,261.3
XS GIS Cut Line= 2
     1648077.913      277746.562      1648158.42      278169.301
#Sta/Elev= 27
       0     910     9.8  908.11    19.6  905.23    29.3  901.87    39.1  899.32
    48.9  897.88    68.5  896.25    78.2  895.34      88   894.3   136.9  888.53
     176  884.14   185.8  883.33   195.6  883.12   205.4   883.1   215.2   883.1
   264.1  883.14   273.8  883.56   283.6   885.5   293.4  889.44   303.2  893.91
     313  898.18   352.1  914.25   381.4  926.55   391.2  931.15     401  936.53
   410.8  941.53   430.3     950
#Mann= 3 , 0 , 0
       0     .06       0   195.6    .045       0   215.2     .06       0
Bank Sta=195.6,215.2
XS Rating Curve= 0 ,0
Exp/Cntr=0.3,0.1

Type RM Length L Ch R = 1 ,5304.5  ,303.7,306.7,309.5
XS GIS Cut Line= 3
     1647900.749      277710.047     1647847.078      278038.659
      1648006.88      278301.156
#Sta/Elev= 30
       0     960    29.4   948.3    58.8  935.79    88.1  922.37   127.3  903.45
   146.9  895.02   156.7  891.27   166.5  888.33   200.3  883.32   205.7   882.7
   215.3  883.18     235  885.13   274.2  886.77   371.4  891.86   400.2  896.21
   409.8  898.11   419.4  901.35     429  905.39   438.6  910.28   448.2  916.54
   467.4  930.31     477  934.97   486.6  936.53   496.2  938.63   515.4  945.52
     525  948.32   544.2  953.56     573  960.38   592.3  965.38   640.3     980
#Mann= 3 , 0 , 0
       0     .06       0   200.3    .045       0   215.3     .06       0
Bank Sta=200.3,215.3
XS Rating Curve= 0 ,0
Exp/Cntr=0.3,0.1

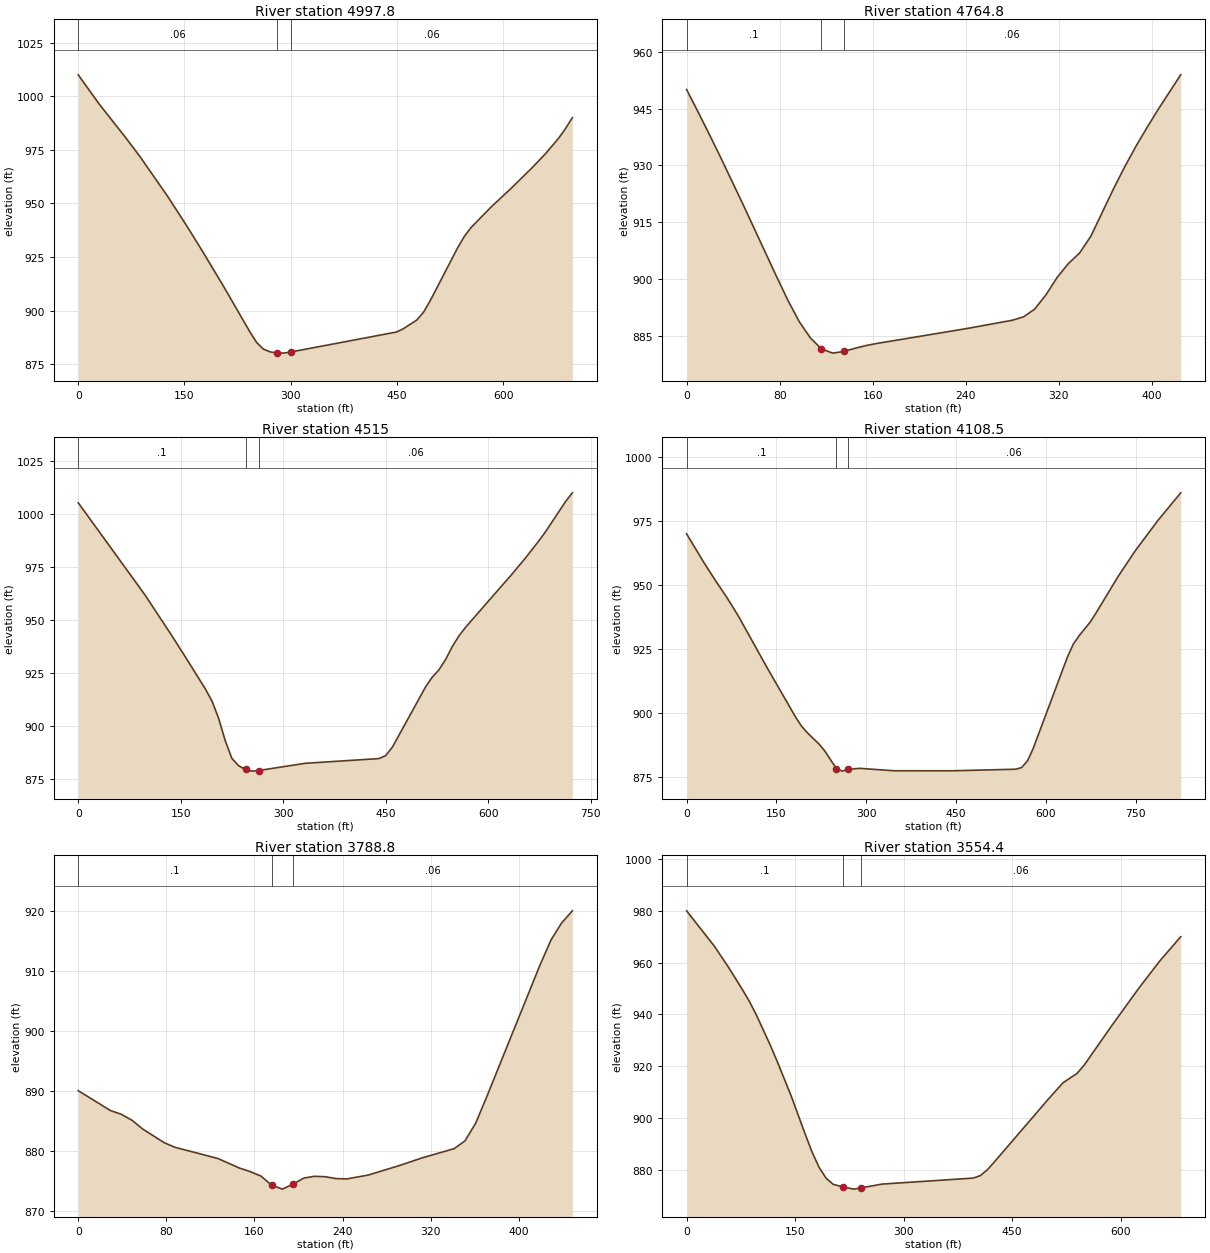
Type RM Length L Ch R = 1 ,4997.8  ,232.2,233.1,233.7
XS GIS Cut Line= 4
     1647604.092      277562.226     1647588.511      277804.183
     1647536.071      278004.259      1647369.26       278188.32
#Sta/Elev= 30
       0    1010    29.1  996.58    67.9   980.3    87.3  971.79   126.1  953.37
   155.2  938.49   174.6  928.12   203.7  912.15   242.5  890.01   251.9  885.12
   261.3  882.05   270.7  880.76   280.1  880.24   289.5  880.15   299.9  880.67
   449.3  889.99   458.8  891.47     478  895.58   487.5   899.2   497.1  904.67
   535.3  929.02   544.8  934.42   554.4  938.65     583  948.34   611.7  957.18
   640.4  966.49   659.5  973.08   678.6  980.53   688.1  984.96   697.7     990
#Mann= 3 , 0 , 0
       0     .06       0   280.1    .045       0   299.9     .06       0
Bank Sta=280.1,299.9
XS Rating Curve= 0 ,0
Exp/Cntr=0.3,0.1

Type RM Length L Ch R = 1 ,4764.8  ,249.9,249.8,249.7
XS GIS Cut Line= 2
     1647398.787      277653.514     1647266.359      278057.065
#Sta/Elev= 30
       0     950     9.6  944.26    19.3  938.34      29  932.28    48.3  919.86
    77.2  900.81    86.9  894.58    96.5  889.01   106.2  884.64   115.8  881.69
   125.5  880.55   135.1  880.98   144.8  881.83   154.4  882.55   164.1  883.13
   241.3  887.05   279.9  889.21   289.6  890.11   299.2  892.15   308.9  895.92
   318.5   900.5   328.2  904.17   337.8  906.93   347.5  911.37   366.8  923.75
   376.5   929.6   386.1  934.98   395.8  940.01   405.4   944.8   424.7  953.88
#Mann= 3 , 0 , 0
       0      .1       0   115.8    .045       0   135.1     .06       0
Bank Sta=115.8,135.1
XS Rating Curve= 0 ,0
Exp/Cntr=0.3,0.1

Type RM Length L Ch R = 1 ,4515    ,412.7,406.5,400
XS GIS Cut Line= 3
     1647196.915      277466.787     1647055.408       277904.22
     1647097.021      278164.576
#Sta/Elev= 30
       0  1005.3    97.8   961.8     137  942.62   156.5  932.78   185.9  917.61
   195.6  911.91   205.4  903.79   215.2   893.1     225  884.71   234.8  881.29
   244.9  879.53   254.3  878.74   264.1  879.03   332.6  882.44   440.2  884.65
     450  886.04   459.8  889.99   508.6  918.51   518.3  923.07   528.1  926.51
   537.9  931.41   547.6  937.45   557.4  942.53   567.2  946.62   635.5  971.82
   655.1   979.4   674.6  987.44   684.4  991.76   713.6 1005.94   723.4 1009.99
#Mann= 3 , 0 , 0
       0      .1       0   244.9    .045       0   264.1     .06       0
Bank Sta=244.9,264.1
XS Rating Curve= 0 ,0
Exp/Cntr=0.3,0.1

Type RM Length L Ch R = 1 ,4108.5  ,327.2,319.7,311.2
XS GIS Cut Line= 4
     1646581.718      277413.205     1646731.269      277562.605
     1646719.484      277949.426     1646813.234      278156.023
#Sta/Elev= 30
       0     970    28.8   958.8      48  951.78    67.3  945.08    86.5   937.8
   134.5  917.58   182.6  898.05   192.2  894.65   201.8   892.1   221.1  887.74
   230.7  885.03   250.1  878.13   259.8  877.11   269.4  877.81   288.8   878.2
   346.8  877.25   443.6  877.24     550  877.86   559.7  878.53   569.4  881.12
     579  886.03   636.2  921.84   645.7  926.74   655.1  929.96     674  935.42
   683.5  938.87   721.3  953.52   749.6  963.44   787.4  975.28   825.3  986.05
#Mann= 3 , 0 , 0
       0      .1       0   250.1    .045       0   269.4     .06       0
Bank Sta=250.1,269.4
XS Rating Curve= 0 ,0
Exp/Cntr=0.3,0.1

Type RM Length L Ch R = 1 ,3788.8  ,236.2,234.4,227.9
XS GIS Cut Line= 2
     1646444.074      277609.132     1646601.553      278029.159
#Sta/Elev= 30
       0     890    29.3  886.68      39  886.07    48.8  885.07    58.5  883.61
      78  881.33    87.8  880.56   126.8  878.69   146.3   877.1     156  876.51
   165.8  875.77   175.5  874.25   185.3  873.58     195  874.41   204.8  875.42
   214.5  875.72   224.3  875.65     234  875.34   243.8  875.28   263.3  875.93
   292.6  877.57     312  878.78   341.3  880.33   351.1  881.63   360.8  884.56
   370.6  888.86   419.3  910.99   429.1   915.1   438.8  917.96   448.6     920
#Mann= 3 , 0 , 0
       0      .1       0   175.5    .045       0     195     .06       0
Bank Sta=175.5,195
XS Rating Curve= 0 ,0
Exp/Cntr=0.3,0.1

Type RM Length L Ch R = 1 ,3554.4  ,248.7,246.4,248.3
XS GIS Cut Line= 4
     1646186.278      277629.737     1646288.929      277744.565
      1646385.02      277987.792     1646522.813      278217.103
#Sta/Elev= 30
       0     980    38.5  966.32    57.8  958.28      77  949.69    86.6  945.14
    96.3  939.92   115.5  928.29   125.1     922   144.4   908.7   163.7  894.03
   173.4  886.95   183.1  881.06   192.8  876.85   202.4  874.51   216.3  873.44
   231.3  872.62   241.2   873.1   270.2  874.56   396.2  876.88   405.9  877.82
   415.5     880   425.1  882.99   501.5   907.8   520.6   913.7   539.8  917.28
   549.3  920.33   587.5  935.58   625.7  950.34   654.4  960.73   683.1     970
#Mann= 3 , 0 , 0
       0      .1       0   216.3    .045       0   241.2     .06       0
Bank Sta=216.3,241.2
XS Rating Curve= 0 ,0
Exp/Cntr=0.3,0.1

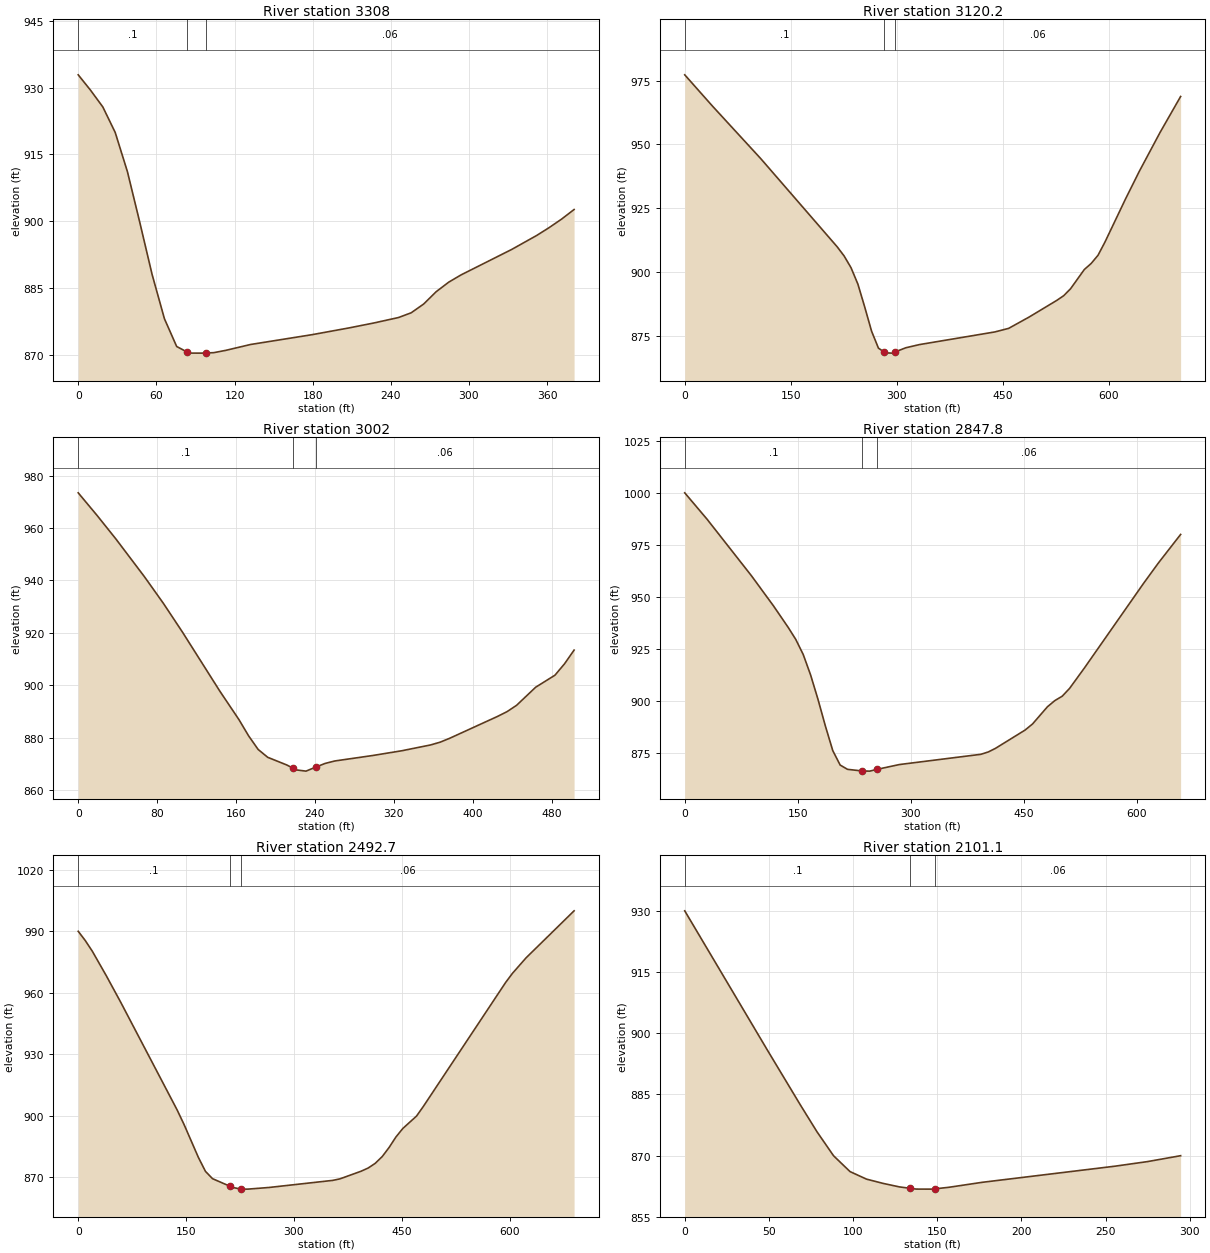
Type RM Length L Ch R = 1 ,3308    ,185.5,187.8,190
XS GIS Cut Line= 3
     1646052.128      277833.169     1646169.033      278038.539
     1646238.283      278165.287
#Sta/Elev= 30
       0  932.88     9.4  929.45    18.9  925.66    28.4  919.93    37.8   911.1
    47.3  899.69    56.7  888.04    66.2  878.06    75.6  871.82    83.2  870.64
    85.1  870.34    94.5  870.33    98.2  870.37     104  870.43   113.4  870.96
   132.3  872.27   179.6  874.48     208     876   226.9   877.1   245.9  878.33
   255.6  879.39   265.2  881.36   274.8  884.13   284.5  886.29   294.1  887.94
   332.6   893.6   351.9  896.76   361.5  898.53   371.1  900.45   380.7  902.61
#Mann= 3 , 0 , 0
       0      .1       0    83.2    .045       0    98.2     .06       0
Bank Sta=83.2,98.2
XS Rating Curve= 0 ,0
Exp/Cntr=0.3,0.1

Type RM Length L Ch R = 1 ,3120.2  ,115.9,118.2,120.6
XS GIS Cut Line= 4
     1645942.252      277717.884     1645909.393       277950.77
     1645995.987       278145.63     1646030.081      278396.258
#Sta/Elev= 30
       0  977.27    39.2  965.03   107.8  944.36   215.6  909.92   225.4  906.34
   235.2  901.73   244.9  895.32   254.6  886.31   264.3  876.84     274  870.22
     282   868.7   283.7  868.38   293.4  868.27     297  868.68   312.7  870.37
   332.1  871.62   438.7  876.57   458.2  877.97   487.3  882.43   526.2  888.92
     536  890.76   545.7  893.47   565.2  901.02   574.9  903.39   584.6  906.61
   594.4  911.78   623.5  928.67     643  939.49   672.2  954.64   701.4  968.78
#Mann= 3 , 0 , 0
       0      .1       0     282    .045       0     297     .06       0
Bank Sta=282,297
XS Rating Curve= 0 ,0
Exp/Cntr=0.3,0.1

Type RM Length L Ch R = 1 ,3002    ,154.7,154.1,153.6
XS GIS Cut Line= 3
     1645685.914      277881.593     1645805.534      277992.237
     1645910.852      278315.229
#Sta/Elev= 30
       0  973.47    19.2   964.8    38.3   955.8    67.1  941.45    86.3  931.28
   105.4  920.44   143.8  897.59     163  886.82   172.6  880.73   182.4  875.45
   192.1  872.45   211.5  869.51   217.4  868.37   221.2  867.63   230.9  867.17
   240.6  868.67   250.3  870.11     260  871.04   298.8  873.15     328  874.95
   357.1  877.16   366.8  878.21   376.5   879.7     425  888.05   434.7  889.88
   444.4  892.31   463.8  899.23   483.3  903.81     493  908.16   502.7   913.4
#Mann= 3 , 0 , 0
       0      .1       0   217.4    .045       0   240.6     .06       0
Bank Sta=217.4,240.6
XS Rating Curve= 0 ,0
Exp/Cntr=0.3,0.1

Type RM Length L Ch R = 1 ,2847.8  ,356.8,355.1,353.4
XS GIS Cut Line= 2
     1645596.148      277864.475     1645814.384      278485.802
#Sta/Elev= 30
       0    1000    29.5  987.38    88.5  960.18     118  945.58   137.6   935.2
   147.4  929.57   157.3  922.32   167.1  912.51   176.9   900.8   186.8  887.88
   196.6  876.08   206.4  869.14   216.2  867.09   235.9  866.29   245.7  866.23
   255.6   867.1     285  869.39   393.2  874.31     403  875.43   412.8  877.21
   452.1     886     462  888.95   481.6  897.15   491.4  900.11   501.3  902.25
   511.1  906.02   530.8  915.84   609.4  956.54     629  966.28   658.5     980
#Mann= 3 , 0 , 0
       0      .1       0   235.9    .045       0   255.6     .06       0
Bank Sta=235.9,255.6
XS Rating Curve= 0 ,0
Exp/Cntr=0.3,0.1

Type RM Length L Ch R = 1 ,2492.7  ,382.3,391.6,401
XS GIS Cut Line= 3
     1645276.082      278046.372     1645446.538       278433.36
     1645636.997      278620.289
#Sta/Elev= 30
       0     990     9.8  985.49    19.7  980.22    39.3  968.14      59  955.42
   137.7  902.64   147.5  895.38   167.2  879.49     177  872.71   186.8  869.14
   210.9  865.45   216.4  864.73   226.2  864.08     236  864.03   265.5  864.84
     354   868.3   363.9  869.03   393.4  872.77   403.2  874.32     413   876.6
   422.9  879.96   432.4  884.38   441.9   889.5   451.5  893.67   470.5   899.7
     480  904.41   594.4  964.95     604  969.47     623  977.06   689.7    1000
#Mann= 3 , 0 , 0
       0      .1       0   210.9    .045       0   226.2     .06       0
Bank Sta=210.9,226.2
XS Rating Curve= 0 ,0
Exp/Cntr=0.3,0.1

Type RM Length L Ch R = 1 ,2101.1  ,376.4,376.6,376.9
XS GIS Cut Line= 2
     1644990.297      278207.482     1644990.297      278502.052
#Sta/Elev= 18
       0  930.04    49.1  895.88    68.7  882.43    78.6  875.83    88.4  869.97
    98.2  866.08     108  864.23   117.8  863.19   127.6  862.32   133.9  861.98
   137.5  861.79   147.3  861.78   148.9  861.86   157.1  862.24   176.7  863.45
   255.3  867.39   274.9  868.53   294.6  869.98
#Mann= 3 , 0 , 0
       0      .1       0   133.9    .045       0   148.9     .06       0
Bank Sta=133.9,148.9
XS Rating Curve= 0 ,0
Exp/Cntr=0.3,0.1

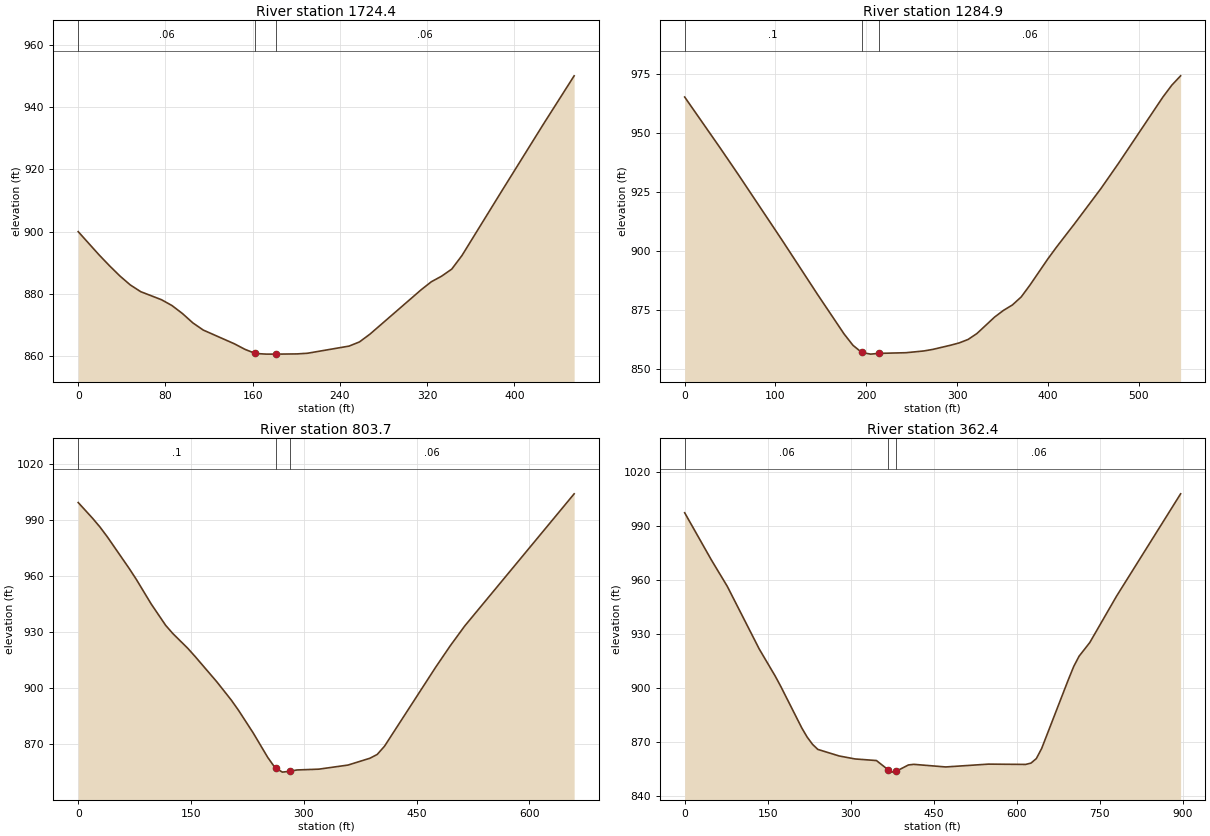
Type RM Length L Ch R = 1 ,1724.4  ,439.2,439.5,439.8
XS GIS Cut Line= 3
        1644618.      278186.142     1644616.422      278463.308
     1644564.567      278633.271
#Sta/Elev= 30
       0     900    19.1  892.56    28.7  889.06    38.2  885.79    47.8  882.89
    57.4  880.73    76.5  878.14      86  876.29    95.6  873.73   105.1  870.74
   114.7  868.42   143.4  863.99   152.9  862.24   162.5  860.91     172  860.71
   178.5   860.7   181.6   860.7   200.7  860.77   210.3  860.98   248.5  863.28
     258  864.62   267.6  867.11   314.6  881.36   323.9  883.92   333.3  885.71
   342.6  887.97     352  892.34   389.4  913.54   426.8  934.55   454.9     950
#Mann= 3 , 0 , 0
       0     .06       0   162.5    .045       0   181.6     .06       0
Bank Sta=162.5,181.6
XS Rating Curve= 0 ,0
Exp/Cntr=0.3,0.1

Type RM Length L Ch R = 1 ,1284.9  ,477.9,481.3,484.4
XS GIS Cut Line= 2
     1644198.776      278119.359     1644193.677      278665.455
#Sta/Elev= 30
       0  965.21      39  943.69    58.5   932.7   107.3  904.58   146.3  881.62
   175.5   864.9   185.3  860.08     195  857.03   204.8  856.34   213.6  856.65
   243.8  856.94   263.3  857.68   273.1  858.33   292.6  860.09   302.3  861.09
   312.1  862.56   321.8  865.06   341.3  872.04   351.1  874.88   360.8  877.14
   370.6  880.57   380.3  885.63   399.8   896.6   409.6  901.74   429.1  911.45
   458.4  926.48   477.9  937.24   526.6  965.21   536.4  970.23   546.1  974.19
#Mann= 3 , 0 , 0
       0      .1       0     195    .045       0   213.6     .06       0
Bank Sta=195,213.6
XS Rating Curve= 0 ,0
Exp/Cntr=0.3,0.1

Type RM Length L Ch R = 1 ,803.7   ,446.2,441.3,436.2
XS GIS Cut Line= 2
     1643772.559      277964.496     1643668.744      278615.933
#Sta/Elev= 30
       0  999.47    19.4   990.9    29.1  986.26    38.8  981.04    67.9  964.07
    77.6  958.07      97  945.13   116.4  933.59   126.1  929.13   145.5  921.42
   155.2  917.07   184.3  903.39   203.7  893.52   213.4  887.98   232.8  875.93
   252.2  862.77   261.9  857.28   263.2  856.97   271.6  854.93   281.3  855.38
     291  856.09   320.1  856.52   358.9  858.72     388  862.37   397.7   864.4
   407.4   868.8   475.3  911.06   494.7  922.55   514.1  933.26   659.7 1004.14
#Mann= 3 , 0 , 0
       0      .1       0   263.2    .045       0   281.3     .06       0
Bank Sta=263.2,281.3
XS Rating Curve= 0 ,0
Exp/Cntr=0.3,0.1

Type RM Length L Ch R = 1 ,362.4   ,385.1,362.4,339.4
XS GIS Cut Line= 4
     1643455.925      277858.086     1643292.417      278034.571
     1643307.989      278429.066      1643458.52      278641.886
#Sta/Elev= 30
       0  997.26    48.1  971.16      77  956.42   134.7  921.65   163.6   906.6
   173.2  901.13   211.7  877.76   221.3  872.75     231  868.72   240.6   865.9
   279.1  862.26     308   860.6   346.5  859.72   367.3  854.68   375.4  853.29
   382.3  853.79   404.3  857.27   413.9  857.61   471.7  856.16   548.7  857.73
   616.1  857.57   625.8  858.31   635.4  860.81     645   866.4   693.3  904.67
     703  911.97   712.6  917.62   731.9  925.19   780.2  950.91   896.1 1007.78
#Mann= 3 , 0 , 0
       0     .06       0   367.3    .045       0   382.3     .06       0
Bank Sta=367.3,382.3
XS Rating Curve= 0 ,0
Exp/Cntr=0.3,0.1

Chan Stop Cuts=-1
Use User Specified Reach Order=0
Composite Channel Slope=5